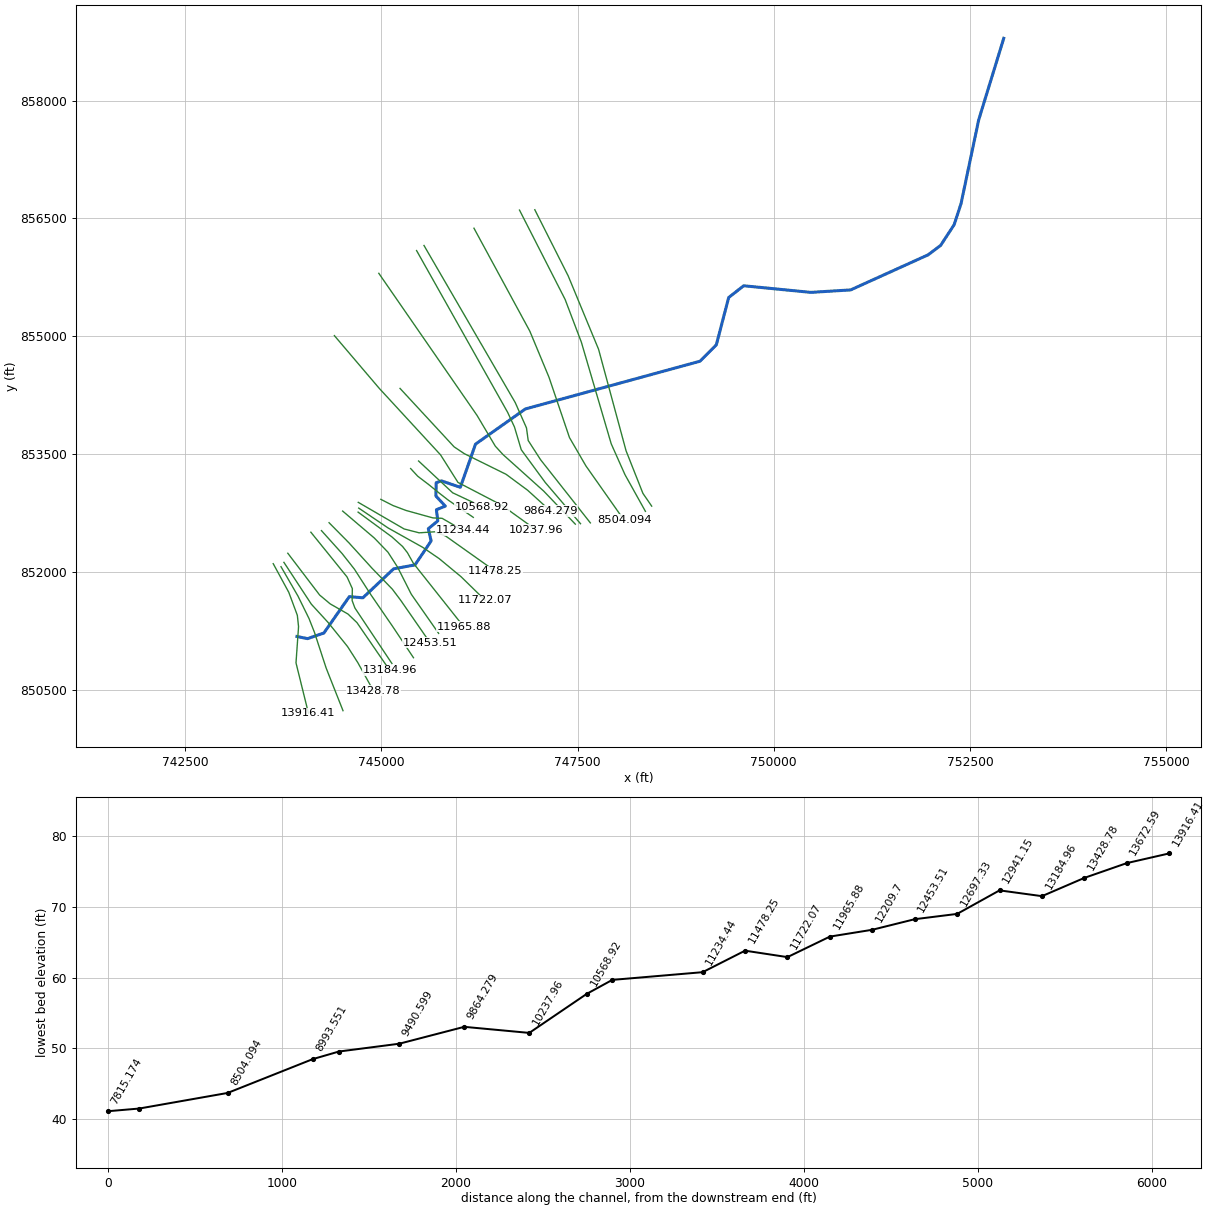
--- 15203_ras.prj (project) ---

Proj Title=15203
Current Plan=p01
Default Exp/Contr=0.3,0.1
English Units
Geom File=g01
Flow File=f01
Plan File=p01
Y Axis Title=Elevation
X Axis Title(PF)=Main Channel Distance
X Axis Title(XS)=Station
BEGIN DESCRIPTION:
RFD model 15203 exported to HEC-RAS
END DESCRIPTION:

--- 15203_ras.p01 (plan) ---

Plan Title=Plan 01
Program Version=4.10
Short Identifier=Plan 01
Geom File=g01
Flow File=f01
Subcritical Flow
Calc Critical at every XS
Secant Critical Depth

--- 15203_ras.f01 (steady flow) ---

Flow Title=Flow 01
Program Version=5.01
Number of Profiles= 6
Profile Names=10yr,25yr,50yr,100yr,100plus,500yr
River Rch & RM=15203,37,13916.41
 1024.64 1678.05 2303.63 2885.19 4212.37 5783.61
River Rch & RM=15203,37,13672.59
 1029.79 1686.63 2315.57 2900.28 4234.41 5810.22
River Rch & RM=15203,37,13428.78
 1569.97    2577 3544.33 4443.69 6487.79 8395.88
River Rch & RM=15203,37,13184.96
 1575.78 2586.71 3557.85 4460.82  6512.8 8424.35
River Rch & RM=15203,37,12941.15
 1581.58 2596.41 3571.37 4477.93 6537.78 8452.78
River Rch & RM=15203,37,12697.33
 1590.04 2610.57 3591.09 4502.91 6574.25 8494.26
River Rch & RM=15203,37,12453.51
 1595.14  2619.1 3602.99 4517.99 6596.27 8519.33
River Rch & RM=15203,37, 12209.7
 1602.89 2632.08 3621.08 4540.92 6629.75 8557.43
River Rch & RM=15203,37,11965.88
 1608.86 2642.07 3635.02 4558.59 6655.54 8586.77
River Rch & RM=15203,37,11722.07
 1614.82 2652.06 3648.95 4576.25 6681.32 8616.07
River Rch & RM=15203,37,11478.25
 1619.21 2659.42 3659.22 4589.28 6700.35 8637.75
River Rch & RM=15203,37,11234.44
 1623.59 2666.78 3669.49 4602.31 6719.37 8659.41
River Rch & RM=15203,37,10715.32
 1631.47 2679.99 3687.94 4625.73 6753.56 8698.35
River Rch & RM=15203,37,10568.92
 1633.21 2682.93 3692.04 4630.93 6761.15 8706.99
River Rch & RM=15203,37,10237.96
 1636.93 2689.16 3700.74 4641.98 6777.28 8725.34
River Rch & RM=15203,37,9864.279
 1642.17 2697.95 3713.02 4657.56 6800.04 8751.23
River Rch & RM=15203,37,9490.599
 1647.18 2706.37 3724.78 4672.48 6821.83 8776.01
River Rch & RM=15203,37,9144.035
 2355.13 3892.02 5378.59 6768.65 9882.2312146.19
River Rch & RM=15203,37,8993.551
 2390.75 3951.88 5462.29 6874.9510037.4312313.48
River Rch & RM=15203,37,8504.094
 2411.41 3986.62 5510.86 6936.65 10127.512410.42
River Rch & RM=15203,37,7995.881
 2449.46 4050.56 5600.28  7050.210293.2912588.48
River Rch & RM=15203,37,7815.174
 2473.41 4090.83 5656.59 7121.7210397.7112700.42
River Rch & RM=15203,37,7659.848
 2475.01 4093.51 5660.34 7126.4810404.6712707.87
River Rch & RM=15203,37,7497.642
 2475.81 4094.85 5662.22 7128.8610408.14 12711.6
River Rch & RM=15203,37,7045.841
 2502.88 4140.37 5725.88 7209.7210526.1912837.96
River Rch & RM=15203,37,6594.039
 2506.66 4146.73 5734.76    722110542.6712855.57
River Rch & RM=15203,37,6142.238
 2515.24 4161.12 5754.89 7246.5510579.97 12895.4
River Rch & RM=15203,37,5781.946
 2524.79 4177.18 5777.34 7275.0510621.57 12939.8
River Rch & RM=15203,37,5684.458
 2525.39 4178.18 5778.74 7276.8310624.1712942.58
River Rch & RM=15203,37,5044.849
 2607.98 4316.98 5972.83  7523.310984.0213325.83
River Rch & RM=15203,37,4870.682
 2609.57 4319.64 5976.54 7528.0210990.9113333.14
River Rch & RM=15203,37,4452.518
 2644.31 4378.01 6058.14 7631.6111142.1513493.56
Boundary for River Rch & Prof#=15203,37,1
Up Type= 0
Dn Type= 2
Boundary for River Rch & Prof#=15203,37,2
Up Type= 0
Dn Type= 2
Boundary for River Rch & Prof#=15203,37,2
Up Type= 0
Dn Type= 2
Boundary for River Rch & Prof#=15203,37,2
Up Type= 0
Dn Type= 2
Boundary for River Rch & Prof#=15203,37,2
Up Type= 0
Dn Type= 2
Boundary for River Rch & Prof#=15203,37,2
Up Type= 0
Dn Type= 2

--- 15203_ras.g01 (geometry) ---

Geom Title=15203
Program Version=4.10

River Reach=15203,37
Reach XY= 30
743926.269239535851176.448043176744060.376034319851149.504315466
744268.709367633851221.118898779744593.145131528 851684.44355154
744765.671173215851669.252579346745157.381242663852038.176190495
745429.733673185852088.089384899745634.811798185852392.993898779
745599.655548215852549.894940495745719.447214872852647.551190451
745702.520131558852790.780357137745815.801381588852836.353273794
745696.009714842852965.259523839745699.915964872853134.530357137
745766.322214872853157.967857122746007.207631528853075.936607122
746200.604019463853625.856652945746835.224122226854073.346545607
    749059.18265 854680.98551099749268.383995175854890.186876461
749425.502099663855491.749303699749616.474242091855641.922793403
750472.377046168855557.721664131750979.321360409855588.971590713
 751966.84883523856036.050177738752125.703001857856155.841844454
752297.578001916856418.862677723752386.119668543856689.696011052
752610.078001916857752.196011052 752929.59043479858791.901242375

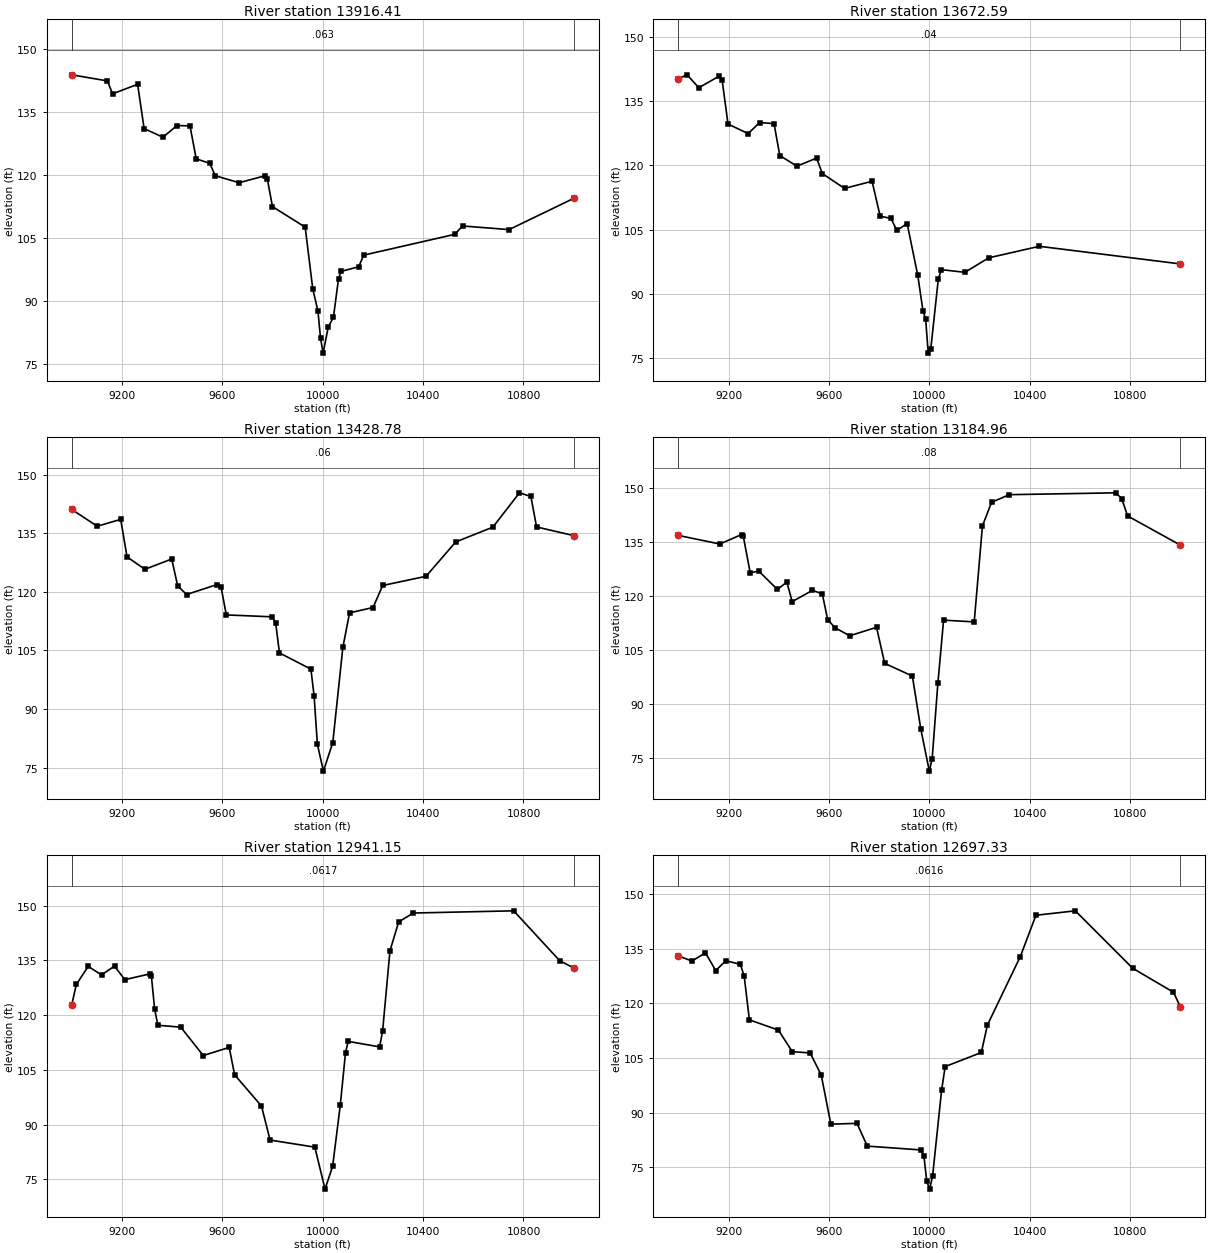
Type RM Length L Ch R = 1 ,13916.41,243.815500,243.815500,243.815500
XS GIS Cut Line= 6
743623.722820417  852103.5226766743822.053587654851738.492995969
743930.622155587851446.886145882743946.174928331851302.618148264
743913.718019853850840.950391766744072.705676767850198.001429408
#Sta/Elev= 30
8999.098143.8765 9141.34142.4276 9161.58 139.3459261.593141.61719287.515131.0701
9362.653128.9953 9418.49131.78579470.401131.70299495.299123.84239549.471122.7859
 9570.97119.81939666.323118.16099768.928119.80089779.078118.9569 9799.32112.4593
9929.685107.5691 9960.1392.776869980.58587.585389990.89881.0975310001.2277.53193
10021.7583.8056410042.2886.0309710062.6395.2729810072.7697.0144410143.13 98.1246
10163.16100.891510526.37105.854810557.08107.846110742.79106.980911000.91114.4382
#Mann= 3 , 0 , 0
8999.098   0.063       08999.098   0.063       011000.91   0.063       0
#XS Ineff= 2 , 0
       0                               0
Bank Sta=8999.098,11000.91
Exp/Cntr=0.3,0.1

Type RM Length L Ch R = 1 ,13672.59,243.815400,243.815400,243.815400
XS GIS Cut Line= 6
743722.714472363852065.405179254743938.349802646851692.164641207
744079.938518825851404.157171615 744149.07255688851228.806933782
744297.414025995850775.796013175744512.434647419850232.417267379
#Sta/Elev= 30
8999.056140.19839034.468141.10419081.054138.09419162.581140.80679174.228139.7977
9197.521129.62169277.823127.38769323.692129.97289381.028129.71889403.962122.2743
9472.011119.78869550.861121.6724 9573.39118.07789662.114114.5937 9771.87116.2702
  9804.3108.11839847.539107.59799870.747104.78159911.719106.40979954.15594.29897
9975.13485.938029985.46184.185359995.77276.1620510006.0977.2016310035.8993.35731
 10047.595.6508210141.9995.0160610237.0198.3967710438.81101.090511000.9796.97939
#Mann= 3 , 0 , 0
8999.056    0.04       08999.056    0.04       011000.97    0.04       0
#XS Ineff= 2 , 0
       0                               0
Bank Sta=8999.056,11000.97
Exp/Cntr=0.3,0.1

Type RM Length L Ch R = 1 ,13428.78,243.815400,243.815400,243.815400
XS GIS Cut Line= 6
743759.751117497852120.479633643744109.403363453851588.054429617
744324.199035932 851353.62300521 744570.44954334851048.823095198
744700.349165039850845.431619581744900.492317146850484.381848935
#Sta/Elev= 30
8999.075141.14399100.612136.84719194.091138.60439219.396128.99599290.667125.8046
9397.573128.44559421.329121.55859456.965 119.3459578.098121.8887 9594.73121.1584
9615.213114.11579798.671 113.623 9812.27111.92289827.199104.36269952.503100.2243
9965.45693.254219978.23980.9917210002.3774.0747510039.8281.3874910079.92105.7769
10106.65114.636910200.22116.014710238.86 121.66110411.52 124.012 10529.9132.8158
10678.15136.619510784.12145.408310829.61144.468110852.36136.656211000.92134.4381
#Mann= 3 , 0 , 0
8999.075    0.06       08999.075    0.06       011000.92    0.06       0
#XS Ineff= 2 , 0
       0                               0
Bank Sta=8999.075,11000.92
Exp/Cntr=0.3,0.1

Type RM Length L Ch R = 1 ,13184.96,243.815400,243.815400,243.815400
XS GIS Cut Line= 6
743809.273620993 852236.76689169744215.007254697851704.363779936
744349.773292501851591.597009941744576.250900303851462.325273894
744690.713253941851352.653777047745107.234387326850746.727724567
#Sta/Elev= 30
8999.104136.74289164.848134.36819251.421 136.9729258.509136.5027 9286.05 126.388
9320.021126.87599394.478121.79399432.181123.8246 9453.35 118.4119534.339121.5479
9573.425120.55219595.074113.42639624.704111.16219682.801108.96259789.707111.3062
9822.235101.32789932.56797.809079966.38783.0864710000.2271.4933610011.5774.97432
10034.2795.8206910057.07113.2874 10179.2112.803510211.96139.353910248.35145.9124
10318.79148.020210743.43148.532410767.19146.952510790.76142.1294 11000.9134.0712
#Mann= 3 , 0 , 0
8999.104    0.08       08999.104    0.08       0 11000.9    0.08       0
#XS Ineff= 2 , 0
       0                               0
Bank Sta=8999.104,11000.9
Exp/Cntr=0.3,0.1

Type RM Length L Ch R = 1 ,12941.15,243.815500,243.815500,243.815500
XS GIS Cut Line= 6
744103.078736654 852504.45645829 744564.46245296 851934.16241615
744631.501971428851785.968740392744628.828133094 851634.19403684
 744663.60201163851539.964982113745135.485488299 850833.29401936
#Sta/Elev= 30
8999.127122.84829017.283128.39549064.697133.3512 9117.73131.02299169.586133.4318
9210.538129.71669310.004131.28249316.477130.7094 9329.48121.66689342.484117.2099
 9433.51116.70689523.301108.9244 9626.78111.14819648.377 103.6389755.51695.07596
  9789.885.757069968.22583.8130610008.8672.3109410039.1578.5738310069.56 95.2759
10090.52109.745210101.26112.798410226.48111.289310238.41115.654510267.67137.5981
10302.35145.526210360.22147.973810761.01148.577410944.47134.903111000.83132.9029
#Mann= 3 , 0 , 0
8999.127  0.0617       08999.127  0.0617       011000.83  0.0617       0
#XS Ineff= 2 , 0
       0                               0
Bank Sta=8999.127,11000.83
Exp/Cntr=0.3,0.1

Type RM Length L Ch R = 1 ,12697.33,243.815400,243.815400,243.815400
XS GIS Cut Line= 6
744237.820998722852524.847857257744501.442965422852232.182361207
744656.783412612852035.346123161744866.753343629851709.555052609
745152.086396303851293.955492747745410.150970468 850906.63744573
#Sta/Elev= 30
8999.047133.0618 9053.96131.65419107.545133.92549148.309129.05359189.073131.7333
9246.941130.75629262.082127.49599282.663115.50829398.579 112.6779453.926106.7469
9524.907106.41239569.106100.36079607.53386.843149711.752 87.05569752.99780.80262
9966.88879.754569978.51278.138779990.09771.0893710001.6668.9872510013.3672.67122
10049.1896.1850910063.34102.651910207.62106.532810231.82114.076910363.11132.9004
10425.41144.240310582.38145.454210811.34129.661710973.66 123.08811000.98119.0999
#Mann= 3 , 0 , 0
8999.047  0.0616       08999.047  0.0616       011000.98  0.0616       0
#XS Ineff= 2 , 0
       0                               0
Bank Sta=8999.047,11000.98
Exp/Cntr=0.3,0.1

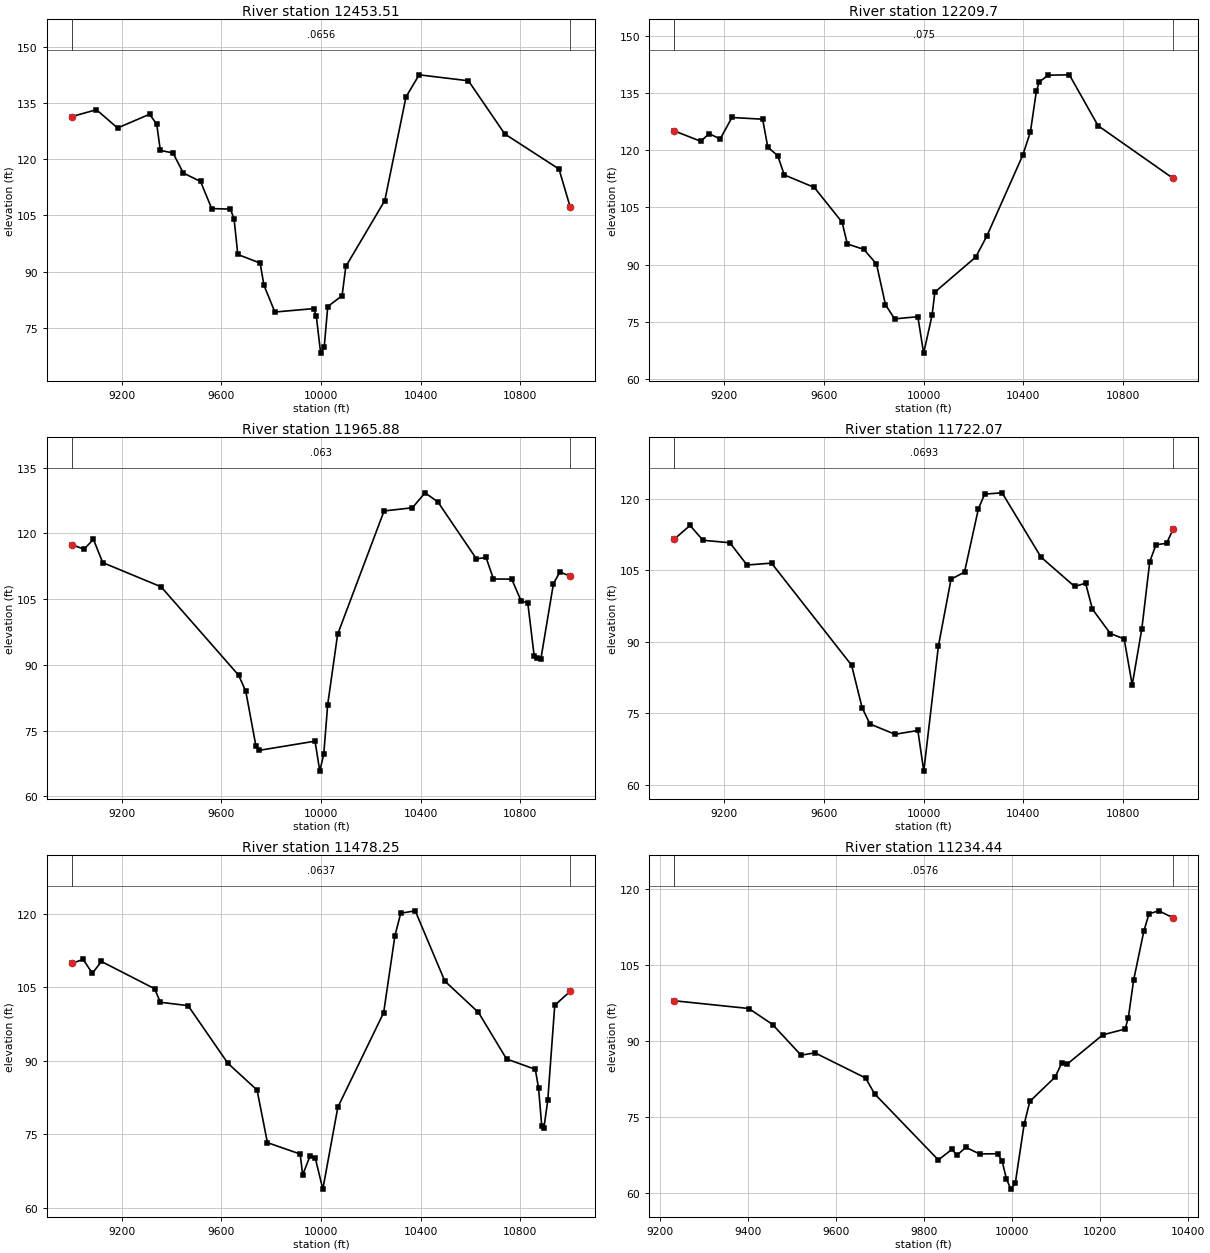
Type RM Length L Ch R = 1 ,12453.51,243.815400,243.815400,243.815400
XS GIS Cut Line= 6
744334.611862648852625.583012763744587.830385742852369.440598373
744880.499610819852047.691364276745141.027350357851778.992191015
745244.677286246851641.304332003 745620.85418052 851098.94077198
#Sta/Elev= 30
8999.019131.33399098.609133.17859183.502128.3026 9312.06131.97239340.781129.3158
9355.142122.33449406.242 121.6329447.213116.29729516.572114.03699561.466106.8016
9636.483 106.6669651.255104.02239666.219 94.55939756.00892.264069770.901 86.3978
9815.04579.202979970.74980.114389981.43678.024799998.787 68.238110013.0469.83751
 10027.380.6725310084.8683.5504610099.7991.3514110256.33108.947610341.48136.6003
10394.12 142.48610591.98140.898210738.02126.7034 10955.6117.353411000.96107.1013
#Mann= 3 , 0 , 0
8999.019  0.0656       08999.019  0.0656       011000.96  0.0656       0
#XS Ineff= 2 , 0
       0                               0
Bank Sta=8999.019,11000.96
Exp/Cntr=0.3,0.1

Type RM Length L Ch R = 1 , 12209.7,243.815400,243.815400,243.815400
XS GIS Cut Line= 6
744508.125137022852773.400749265744911.738209155852430.117547583
745085.488160966 852249.64725544745207.019751184852060.930368227
 745382.97662539851713.814611389745730.730387373851216.558564413
#Sta/Elev= 30
8999.048125.05389105.205122.32059138.801124.34069182.804122.92239230.335128.5733
9353.522128.11819374.175120.76599413.941118.55479440.453113.50399560.762110.2225
9672.602101.08649693.38395.383589759.78993.961759810.46990.117279846.55579.45417
9883.35175.730289976.47276.30421 9999.74 66.746910033.5276.6383910044.7582.74291
10209.1191.9717110254.0897.5544410397.78118.697510428.38124.782110452.21135.4637
10464.12137.914410499.96 139.67410584.73 139.76510699.85126.422911000.95 112.612
#Mann= 3 , 0 , 0
8999.048   0.075       08999.048   0.075       011000.95   0.075       0
#XS Ineff= 2 , 0
       0                               0
Bank Sta=8999.048,11000.95
Exp/Cntr=0.3,0.1

Type RM Length L Ch R = 1 ,11965.88,243.815500,243.815500,243.815500
XS GIS Cut Line= 6
744704.724297979852760.102655606745136.668444346852443.546422902
745270.934176406852323.135513575 745332.78494719 852244.34750899
 745407.63924719852110.916268192746049.561619964851302.588215869
#Sta/Elev= 30
8999.138117.4449 9049.32116.41079086.698118.66389124.076113.34689358.387107.8238
9669.67987.655119698.23784.007869739.11571.486639752.05270.519389976.32172.61414
9995.40865.7814310011.3969.6908610027.1880.9721510066.9396.97442 10253.4125.1253
10367.18125.854910417.96129.2628 10469.5127.180910624.15114.203810662.81114.5201
10692.51109.6104 10765.9 109.57410803.49104.619310830.34104.131210856.1192.00582
10866.9191.6042910882.7691.3518610933.43108.5688 10959.2111.205411000.97110.2399
#Mann= 3 , 0 , 0
8999.138   0.063       08999.138   0.063       011000.97   0.063       0
#XS Ineff= 2 , 0
       0                               0
Bank Sta=8999.138,11000.97
Exp/Cntr=0.3,0.1

Type RM Length L Ch R = 1 ,11722.07,243.815400,243.815400,243.815400
XS GIS Cut Line= 6
744712.788242789852811.429193815745087.433599712852558.168726633
745526.302195288 852312.91709027745738.266463314852167.742316374
 746016.38994114851937.647566871746323.218054727851638.659804841
#Sta/Elev= 30
8999.039111.5181 9062.04114.36269113.922111.26069221.795110.74289290.782106.0763
9389.088106.47179710.55685.074589752.87476.152249784.374 72.76299884.72670.60487
9976.59771.4018710000.33 62.884110059.1989.1535210109.74103.099610163.83104.5939
10219.81117.902810244.88120.934410314.64121.201210471.02107.722310605.81101.5834
10649.93102.257310677.3596.8223110749.1591.7160810804.73 90.592910837.0880.93885
10875.7292.7323610907.52106.791510932.52110.317710975.11110.629611000.97113.5346
#Mann= 3 , 0 , 0
8999.039  0.0693       08999.039  0.0693       011000.97  0.0693       0
#XS Ineff= 2 , 0
       0                               0
Bank Sta=8999.039,11000.97
Exp/Cntr=0.3,0.1

Type RM Length L Ch R = 1 ,11478.25,243.815400,243.815400,243.815400
XS GIS Cut Line= 6
744706.992754437852884.640462438 745291.25577375852545.745795973
745482.418272719852496.608857739745679.803257082852509.523982664
745820.614649315852455.586580089746452.977118803852007.195994477
#Sta/Elev= 30
8999.132109.83939045.606110.65039082.289107.81689118.882110.22979332.099104.6757
9355.609101.90739466.721101.22319626.20689.480629743.59983.997849785.17873.27376
9916.67170.952119926.67366.691739956.82870.618089977.12170.1444110007.5663.79387
10067.9480.5313610251.6699.7752310297.03115.495810320.21120.071610378.44120.5607
10497.08106.238610632.3799.8309210744.9590.3466110860.4988.2252610873.4984.37098
 10886.576.5818510894.8176.2031310910.4581.9314310938.51101.294411000.89104.1661
#Mann= 3 , 0 , 0
8999.132  0.0637       08999.132  0.0637       011000.89  0.0637       0
#XS Ineff= 2 , 0
       0                               0
Bank Sta=8999.132,11000.89
Exp/Cntr=0.3,0.1

Type RM Length L Ch R = 1 ,11234.44,519.118200,519.118200,519.118200
XS GIS Cut Line= 6
744994.293731828852922.789983734745148.906703055852844.110586882
745315.760185093852781.164010644745658.247120798852686.393784478
745775.121370345852681.245438561746041.537879378852528.003580227
#Sta/Elev= 30
9232.48897.907039401.704  96.382 9455.6993.226579520.32987.174989551.98987.63782
9666.82782.682279687.49779.551019832.30766.511029863.54968.632099873.96367.39806
9894.79168.993869926.03367.693489966.88567.736089976.96666.378989987.02262.75732
9997.07860.7560210007.1661.9739210027.2273.5328610040.1378.0590310097.4682.84455
10113.1585.6944210124.4885.37264 10205.891.1823410256.48 92.325910263.9994.56874
10276.02101.998310299.12111.610910310.87115.052510333.18115.647710365.55114.2784
#Mann= 3 , 0 , 0
9232.488  0.0576       09232.488  0.0576       010365.55  0.0576       0
#XS Ineff= 2 , 0
       0                               0
Bank Sta=9232.488,10365.55
Exp/Cntr=0.3,0.1

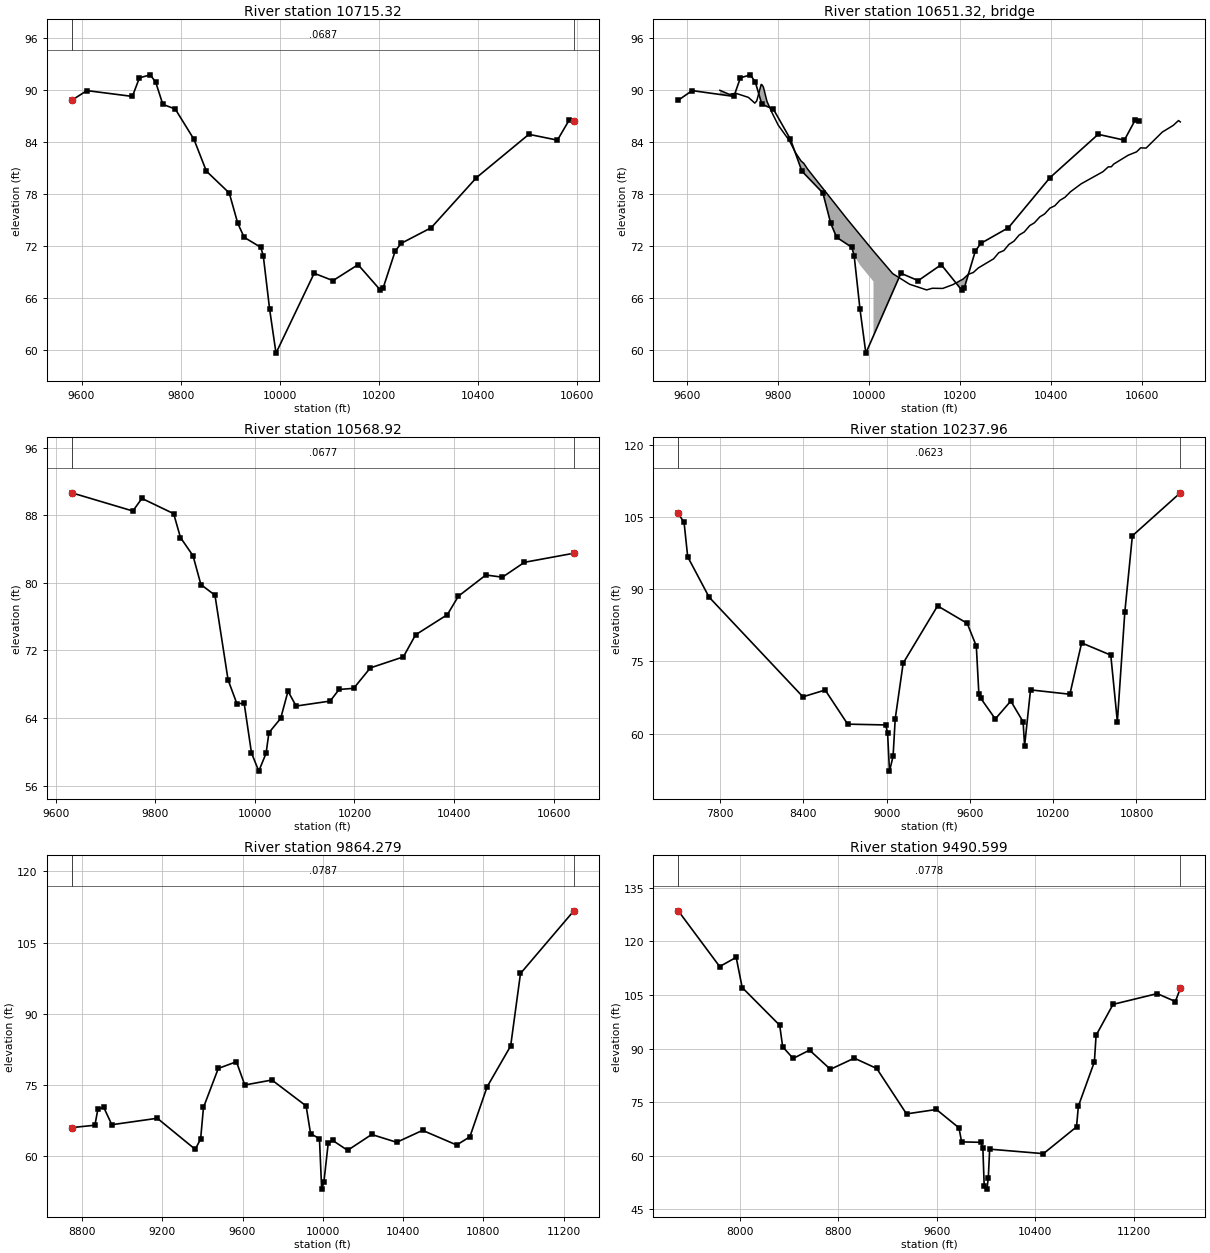
Type RM Length L Ch R = 1 ,10715.32,146.402500,146.402500,146.402500
XS GIS Cut Line= 6
745374.223390586853314.845796137745464.651599147853217.085570665
745605.276599088853110.141126232745736.943265804853003.474459545
745854.373821326852912.155015142746172.327543297852693.561831267
#Sta/Elev= 30
9580.22988.840029610.82689.953849702.61889.283449716.84491.425559738.96391.77408
9749.88490.89475 9764.0988.369079789.21687.827159826.90684.340859852.03280.66419
9898.237 78.14269915.45374.643859928.32373.029169961.78171.878189966.93270.91801
9979.80264.723839992.67259.6670910069.73 68.880510107.7368.02983 10158.469.87059
10203.6566.9235810209.0467.1832810233.3171.4382910245.4572.3319910306.1274.13593
10397.4279.9114910503.3384.9097310560.9684.2377310585.2386.6075810594.1386.42087
#Mann= 3 , 0 , 0
9580.229  0.0687       09580.229  0.0687       010594.13  0.0687       0
#XS Ineff= 2 , 0
       0                10083.34       0
Bank Sta=9580.229,10594.13
Exp/Cntr=0.3,0.1

Type RM Length L Ch R = 3 ,10651.32,,,
BEGIN DESCRIPTION:
END DESCRIPTION:
Bridge Culvert--1,0,-1,-1, 0
Deck Dist Width WeirC Skew NumUp NumDn MinLoCord MaxHiCord MaxSubmerge Is_Ogee
54.828600,36.745300,2.6,0, 60, 60, , , 0.95, 0, 0,0,,
 9671.77 9692.50 9706.51 9734.54 9748.56 9752.83 9762.57 9764.93 9767.49 9775.28
 9787.72 9800.17 9825.05 9837.50 9849.94 9856.53 9864.45 9951.38 9951.3810009.45
10009.4510051.6710088.9610126.2510138.6810161.6710184.0610206.4410217.6410228.83
10240.0210273.6010284.8010295.9910307.1810318.3810329.5710340.7710352.9410363.15
10375.2010385.5410397.4610407.9310419.1210430.3110442.2010465.9910513.9210525.44
10532.4010537.3310569.3710587.8510596.7810608.6810644.3510668.1310680.0210683.94
   89.99   89.52   89.65   89.17   88.51   88.77   90.67   90.59   90.35   88.71
   87.26   85.96   84.14   82.84   81.85   81.54   80.91   75.14   75.14   71.43
   71.43   68.84   67.61   66.96   67.15   67.13   67.57   68.21   68.75   68.97
   69.50   70.55   71.25   71.50   72.21   72.59   73.29   73.64   74.38   74.70
   75.39   75.72   76.40   76.66   77.29   77.64   78.27   79.20   80.60   81.15
   81.17   81.47   82.50   82.89   83.35   83.32   85.17   85.93   86.50   86.34
 -910.01 -910.48 -910.35 -910.83 -911.49 -911.23 -909.33 -909.41 -909.65 -911.29
 -912.74 -914.04 -915.86 -917.16 -918.15 -918.46 -919.09 -924.86   71.64   67.93
 -928.57 -931.16 -932.39 -933.04 -932.85 -932.87 -932.43 -931.79 -931.25 -931.03
 -930.50 -929.45 -928.75 -928.50 -927.79 -927.41 -926.71 -926.36 -925.62 -925.30
 -924.61 -924.28 -923.60 -923.34 -922.71 -922.36 -921.73 -920.80 -919.40 -918.85
 -918.83 -918.53 -917.50 -917.11 -916.65 -916.68 -914.83 -914.07 -913.50 -913.66
 9671.77 9692.50 9706.51 9734.54 9748.56 9752.83 9762.57 9764.93 9767.49 9775.28
 9787.72 9800.17 9825.05 9837.50 9849.94 9856.53 9864.45 9951.23 9951.2310009.31
10009.3110051.6710088.9610126.2510138.6810161.6710184.0610206.4410217.6410228.83
10240.0210273.6010284.8010295.9910307.1810318.3810329.5710340.7710352.9410363.15
10375.2010385.5410397.4610407.9310419.1210430.3110442.2010465.9910513.9210525.44
10532.4010537.3310569.3710587.8510596.7810608.6810644.3510668.1310680.0210683.94
   89.99   89.52   89.65   89.17   88.51   88.77   90.67   90.59   90.35   88.71
   87.26   85.96   84.14   82.84   81.85   81.54   80.91   75.15   75.15   71.44
   71.44   68.84   67.61   66.96   67.15   67.13   67.57   68.21   68.75   68.97
   69.50   70.55   71.25   71.50   72.21   72.59   73.29   73.64   74.38   74.70
   75.39   75.72   76.40   76.66   77.29   77.64   78.27   79.20   80.60   81.15
   81.17   81.47   82.50   82.89   83.35   83.32   85.17   85.93   86.50   86.34
 -910.01 -910.48 -910.35 -910.83 -911.49 -911.23 -909.33 -909.41 -909.65 -911.29
 -912.74 -914.04 -915.86 -917.16 -918.15 -918.46 -919.09 -924.85   71.65   67.94
 -928.56 -931.16 -932.39 -933.04 -932.85 -932.87 -932.43 -931.79 -931.25 -931.03
 -930.50 -929.45 -928.75 -928.50 -927.79 -927.41 -926.71 -926.36 -925.62 -925.30
 -924.61 -924.28 -923.60 -923.34 -922.71 -922.36 -921.73 -920.80 -919.40 -918.85
 -918.83 -918.53 -917.50 -917.11 -916.65 -916.68 -914.83 -914.07 -913.50 -913.66
BR Coef=-1 , 0 , 0 ,, 0 ,,,0.8,0,1,0,
WSPro=,,,, 1 ,,,, 0 ,,,, 0 ,,,,-1 ,-1 ,-1 , 0 , 0 , 0 , 0 , 0
BC Design=,, 0 ,, 0 ,,,,,,

Type RM Length L Ch R = 1 ,10568.92,330.958000,330.958000,330.958000
XS GIS Cut Line= 5
745475.249775019853411.033239675745824.850627601853085.400294259
 745909.57284981853006.233627588746206.696111619852866.376065031
746280.178825051852820.969293997
#Sta/Elev= 30
9632.294 90.64779754.946 88.49649773.192 89.98469836.94288.181639850.60885.35712
9875.89583.193389891.60679.794569919.911 78.5239 9946.2768.496659963.92665.69339
9978.598 65.7236 9993.2759.8575310007.9457.7019610022.6159.8184710028.27 62.2436
10051.96 63.952410066.6367.1640610082.93 65.406910151.3265.9956810169.2367.37135
10198.5267.5012210232.0169.9219310298.3271.2256910322.8373.8348910386.7476.22565
10408.8578.4112310464.1180.9199910497.2780.6600810541.4882.4212510640.7883.49578
#Mann= 3 , 0 , 0
9632.294  0.0677       09632.294  0.0677       010640.78  0.0677       0
#XS Ineff= 2 , 0
       0                               0
Bank Sta=9632.294,10640.78
Exp/Cntr=0.3,0.1

Type RM Length L Ch R = 1 ,10237.96,373.679500,373.679500,373.679500
XS GIS Cut Line= 6
744402.402037382855007.288908079744972.023426771854338.298233941
745755.754880607853488.507247522745977.240902752853138.164878771
746534.361310601852848.917162001746970.020851612852535.814493909
#Sta/Elev= 30
7499.163105.7518 7541.26 103.8697567.33596.735947721.40488.350488397.20467.62656
8557.47969.038558719.57461.946188993.30861.780179007.06960.162499020.82952.18016
9046.73355.23393 9062.1163.043129119.521 74.63429367.37586.531939580.69482.90089
9646.35778.173069664.66268.235179676.856 67.3816 9783.0663.028379894.74166.74811
9983.32962.435519994.11857.4393110036.8169.0679710320.3768.1640610404.9778.83691
10614.9776.2923910662.2462.4711410716.0585.2285510770.46101.097511115.77110.0332
#Mann= 3 , 0 , 0
7499.163  0.0623       07499.163  0.0623       011115.77  0.0623       0
#XS Ineff= 2 , 0
       09878.905        10164.87       0
Bank Sta=7499.163,11115.77
Exp/Cntr=0.3,0.1

Type RM Length L Ch R = 1 ,9864.279,373.679500,373.679500,373.679500
XS GIS Cut Line= 6
745239.066023278854334.997102064745928.114845824853590.917377791
746058.016599072853504.204745476746589.906589267853241.699805596
746864.845470989853038.336414236747156.667251998852773.729597926
#Sta/Elev= 30
 8749.0966.000458864.25166.503788879.41769.92159  8908.770.244348948.60366.61017
9175.36867.967399364.15761.426489391.12763.586819405.38570.249499479.25378.47062
9569.54879.876739611.18374.978859746.46576.026699916.82770.565999939.09664.71135
9983.30663.676419994.35853.0374810005.3254.5019410026.8362.6635210048.3363.32175
10123.6161.2132910243.6464.5510810368.1362.9051710497.1165.4190510667.0862.33658
10732.7864.0603710818.5474.5794110936.0683.2001810985.0298.4713611250.92111.6751
#Mann= 3 , 0 , 0
 8749.09  0.0787       0 8749.09  0.0787       011250.92  0.0787       0
#XS Ineff= 2 , 0
       09699.329         10422.1       0
Bank Sta=8749.09,11250.92
Exp/Cntr=0.3,0.1

Type RM Length L Ch R = 1 ,9490.599,346.564300,346.564300,346.564300
XS GIS Cut Line= 6
744968.710089394855800.135896499746219.885768439853991.493252605
746452.772012259853599.615756835746551.494032553853492.209264763
747070.613128729853026.568467896747471.810214777852607.094028363
#Sta/Elev= 30
7499.029128.5686 7835.82112.96397969.911115.54658018.671107.09178323.39496.53639
8347.65390.50638 8432.5687.234518565.98689.567478735.53184.19898 8929.8987.31885
9111.81784.433479353.94671.71351    959772.948879780.28267.802819801.62863.87737
9958.74863.755329974.31162.156719985.403 51.443510007.5450.6511210018.5953.82968
10029.7361.8440610466.7260.5828210735.4968.0827910750.4573.8808610880.7186.30074
10894.4493.7040311032.42102.381911391.09105.388711538.49103.179311578.88106.8308
#Mann= 3 , 0 , 0
7499.029  0.0778       07499.029  0.0778       011578.88  0.0778       0
#XS Ineff= 2 , 0
       0 9646.31        10444.01       0
Bank Sta=7499.029,11578.88
Exp/Cntr=0.3,0.1

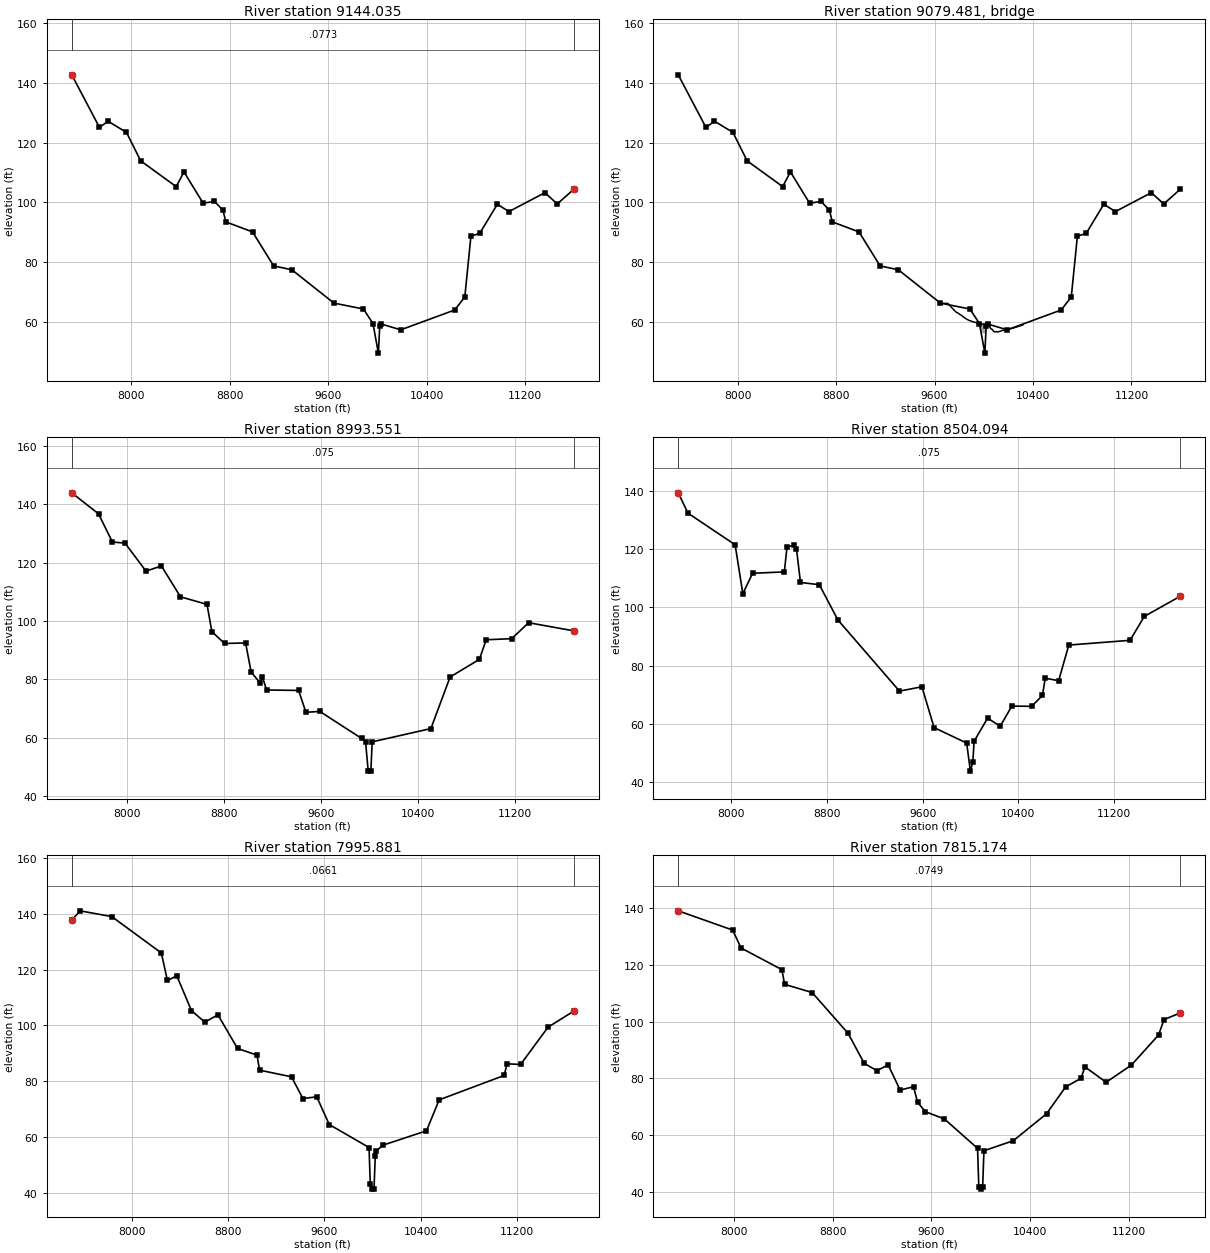
Type RM Length L Ch R = 1 ,9144.035,150.483500,150.483500,150.483500
XS GIS Cut Line= 6
745449.677016467856090.087794289746609.399238765854031.060016513
746696.899238735853843.560016483 746783.01034981853554.671127602
747088.565905362853138.004460931747537.834123671852612.650495961
#Sta/Elev= 30
7517.596142.72427742.779125.10967812.034 127.1937962.088123.44978077.514113.9229
8366.079105.30268429.285110.20258585.25199.737698677.312100.34058746.35897.39876
8769.37393.489948986.61790.126739157.72678.752089306.02177.451359648.23966.28489
9887.56764.324219965.06559.4552910008.9649.5499510019.9958.7286810031.0359.30906
10190.6457.3530910629.3563.9895510711.2568.3754810760.8588.6827310832.2789.65099
10975.68   99.39 11069.796.9435611362.04103.265411462.5399.50073 11597.2104.4239
#Mann= 3 , 0 , 0
7517.596  0.0773       07517.596  0.0773       0 11597.2  0.0773       0
#XS Ineff= 2 , 0
       0                10444.59       0
Bank Sta=7517.596,11597.2
Exp/Cntr=0.3,0.1

Type RM Length L Ch R = 3 ,9079.481,,,
BEGIN DESCRIPTION:
END DESCRIPTION:
Bridge Culvert--1,0,-1,-1, 0
Deck Dist Width WeirC Skew NumUp NumDn MinLoCord MaxHiCord MaxSubmerge Is_Ogee
45.058100,60.367300,2.6,0, 31, 31, , , 0.95, 0, 0,0,,
 9650.97 9658.17 9669.70 9704.27 9715.80 9738.85 9773.42 9796.47 9807.68 9818.69
 9840.70 9862.71 9884.72 9895.72 9906.73 9979.82 9979.8210020.1810020.1810042.60
10057.0810069.0210079.7310085.1410090.4310101.1310111.8410197.4010218.6810239.96
10316.91
   66.08   66.07   66.21   66.21   65.91   64.82   63.35   62.81   62.44   62.22
   61.48   60.88   60.43   60.32   60.09   59.37   59.37   58.98   58.98   58.77
   57.78   57.47   56.92   56.72   56.66   56.75   56.62   57.68   57.75   57.95
   58.96
 -933.92 -933.93 -933.79 -933.79 -934.09 -935.18 -936.65 -937.19 -937.56 -937.78
 -938.52 -939.12 -939.57 -939.68 -939.91 -940.63   56.37   55.98 -941.02 -941.23
 -942.22 -942.53 -943.08 -943.28 -943.34 -943.25 -943.38 -942.32 -942.25 -942.05
 -941.04
 9650.97 9658.17 9669.70 9704.27 9715.80 9738.85 9773.42 9796.47 9807.68 9818.69
 9840.70 9862.71 9884.72 9895.72 9906.73 9979.82 9979.8210020.1810020.1810042.60
10057.0810069.0210079.7310085.1410090.4310101.1310111.8410197.4010218.6810239.96
10316.91
   66.08   66.07   66.21   66.21   65.91   64.82   63.35   62.81   62.44   62.22
   61.48   60.88   60.43   60.32   60.09   59.37   59.37   58.98   58.98   58.77
   57.78   57.47   56.92   56.72   56.66   56.75   56.62   57.68   57.75   57.95
   58.96
 -933.92 -933.93 -933.79 -933.79 -934.09 -935.18 -936.65 -937.19 -937.56 -937.78
 -938.52 -939.12 -939.57 -939.68 -939.91 -940.63   56.37   55.98 -941.02 -941.23
 -942.22 -942.53 -943.08 -943.28 -943.34 -943.25 -943.38 -942.32 -942.25 -942.05
 -941.04
BR Coef=-1 , 0 , 0 ,, 0 ,,,0.8,0,1,0,
WSPro=,,,, 1 ,,,, 0 ,,,, 0 ,,,,-1 ,-1 ,-1 , 0 , 0 , 0 , 0 , 0
BC Design=,, 0 ,, 0 ,,,,,,

Type RM Length L Ch R = 1 ,8993.551,489.457500,489.457500,489.457500
XS GIS Cut Line= 6
745544.121460915856154.671127617746706.621460885854154.671127602
746849.677016467853832.448905379746871.899238735853671.337794289
747029.538127631853426.893349841747663.533210695852623.229131997
#Sta/Elev= 30
7544.961143.97887765.603136.77717880.011127.10317984.497126.71848157.608117.1086
 8284.84118.88868442.184108.29138661.078105.69748700.87796.366248805.33592.28038
 8979.4792.47026  9025.1 82.49499098.86678.738679117.63280.904389152.33276.33079
9417.25776.166119476.95668.667829591.86168.967669936.16759.710629969.708 58.3496
9991.31548.4784110013.1648.53942   1002458.5214610508.5263.0833510666.9180.78038
10908.3586.8163410965.0893.5576511175.2193.9330311314.9999.4104311688.1596.60765
#Mann= 3 , 0 , 0
7544.961   0.075       07544.961   0.075       011688.15   0.075       0
#XS Ineff= 2 , 0
       0                10471.88       0
Bank Sta=7544.961,11688.15
Exp/Cntr=0.3,0.1

Type RM Length L Ch R = 1 ,8504.094,508.212700,508.212700,508.212700
XS GIS Cut Line= 6
746180.699437288856374.909924119746893.124937387855062.291866306
747136.913628463854476.322308349747397.446358381853709.366524931
747606.393032378853349.189069574748092.111827397852659.297629432
#Sta/Elev= 30
7555.273139.42477636.924132.4285 8031.51121.54978095.902104.70988177.338111.7547
8443.006112.22518465.721120.82218521.989121.35298544.495120.25398578.254108.5821
8735.764107.82798891.59695.686399406.70571.209389594.21972.71618 9696.3958.67295
9969.107 53.339610000.04 43.698810020.6346.8542810030.9253.9661410144.3261.93677
10249.5159.12175 10346.566.0601510512.5565.9915710603.1969.7181810626.2575.65503
10738.5674.8048610823.5387.0647811336.0488.6917611456.1396.9352211756.72103.8639
#Mann= 3 , 0 , 0
7555.273   0.075       07555.273   0.075       011756.72   0.075       0
#XS Ineff= 2 , 0
       0                10461.77       0
Bank Sta=7555.273,11756.72
Exp/Cntr=0.3,0.1

Type RM Length L Ch R = 1 ,7995.881,180.707700,180.707700,180.707700
XS GIS Cut Line= 6
746760.891437322856605.328253374747342.297809243855467.122311994
747549.390076697854922.092901021747929.029413313 853630.30406104
748104.124746174853237.695864573748364.892101318852770.024920836
#Sta/Elev= 30
7499.033137.63687568.312140.97667831.526138.92198243.862125.91818294.263116.0749
8372.392117.74458494.138105.32668604.599101.18758714.496103.79088877.502 91.7701
9039.38589.395129060.84384.013949326.27381.641589420.81773.863739535.89274.50593
 9639.7864.594659970.85556.374379981.17943.216919991.50441.4967210012.1641.50014
10022.4953.2463810032.8355.1884310084.5157.1768410448.5362.3540510554.0873.41284
11093.7582.12642   1111986.3021311231.1686.05288 11459.299.3942311673.77105.1283
#Mann= 3 , 0 , 0
7499.033  0.0661       07499.033  0.0661       011673.77  0.0661       0
#XS Ineff= 2 , 0
       0                10463.52       0
Bank Sta=7499.033,11673.77
Exp/Cntr=0.3,0.1

Type RM Length L Ch R = 1 ,7815.174,155.325500,155.325500,155.325500
XS GIS Cut Line= 6
746955.927016467856609.532238752747380.927016467855767.865572065
747768.427016526854832.448905408748118.427016497853540.782238737
 748333.01034984852999.115572065748444.901239663852836.282488525
#Sta/Elev= 30
7545.436138.92367987.413132.15318054.629125.86718386.428118.25678408.613 113.085
8631.818110.20828923.426 95.88239054.879 85.30969157.73782.742149248.41984.78977
9346.10975.946539454.65277.092559487.21671.666839549.93668.347769705.14565.77904
9974.17455.454739984.52141.7030510005.2241.1161610015.5641.9791810025.9154.60152
 10263.958.1283610533.5867.5932610689.3577.0669410813.9680.0630410845.3384.08672
11017.4378.67526 11221.884.6813711442.91 95.286511487.39100.709411619.31 103.057
#Mann= 3 , 0 , 0
7545.436  0.0749       07545.436  0.0749       011619.31  0.0749       0
#XS Ineff= 2 , 0
       0                10461.24       0
Bank Sta=7545.436,11619.31
Exp/Cntr=0.3,0.1