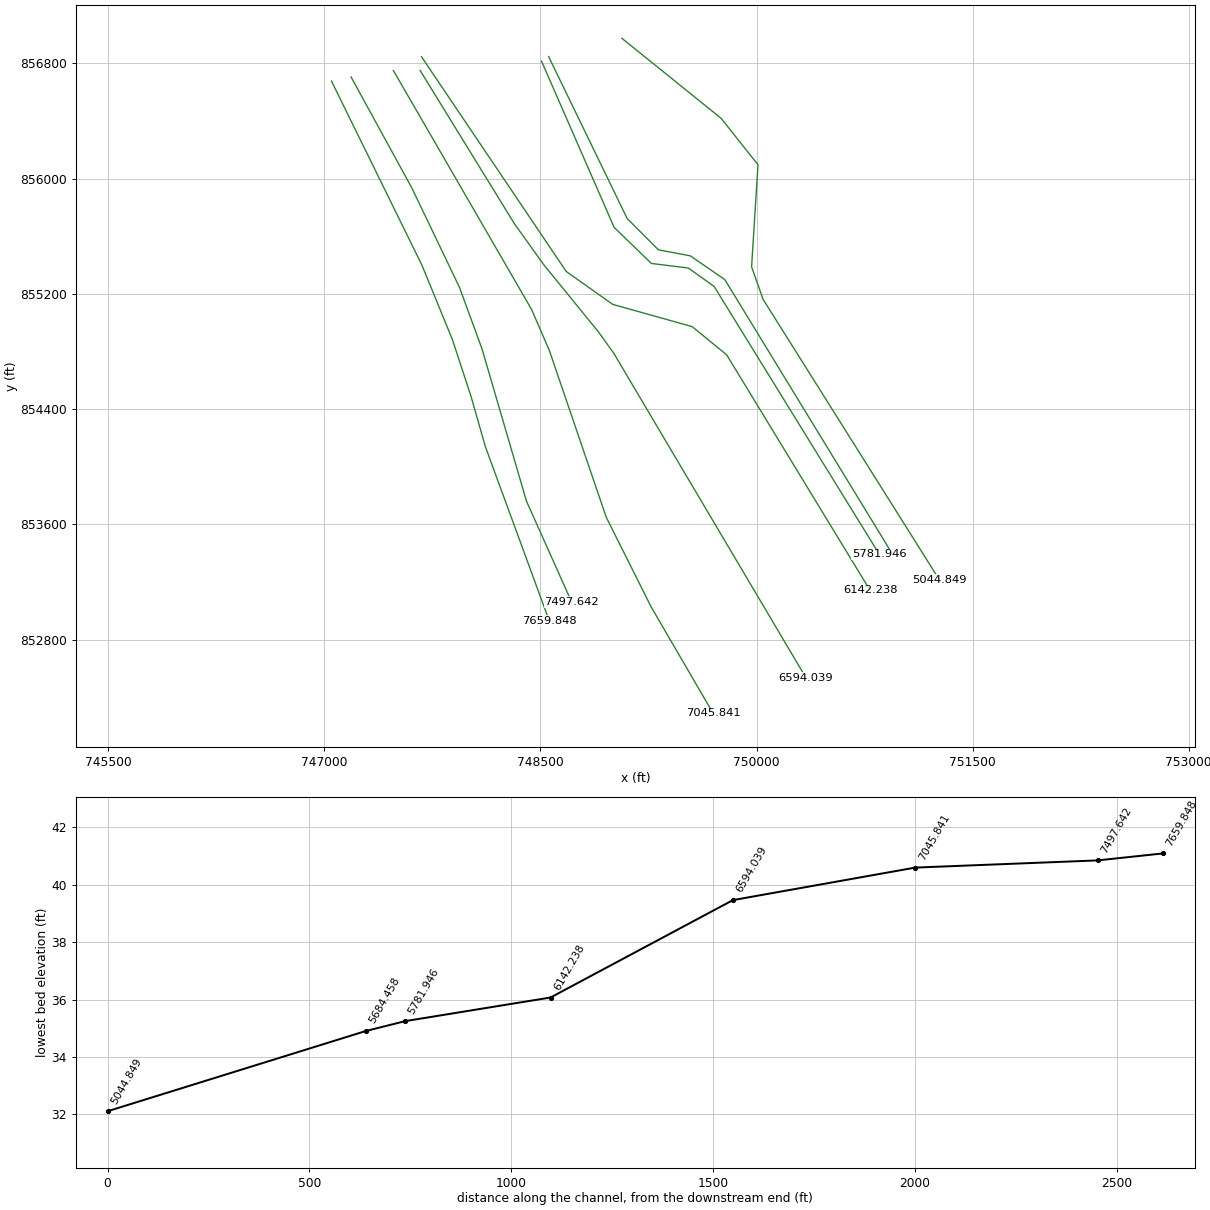
HEC-RAS study 15203_ras.prj: 15203

--- 15203_ras.g01 (geometry) --- (continued)

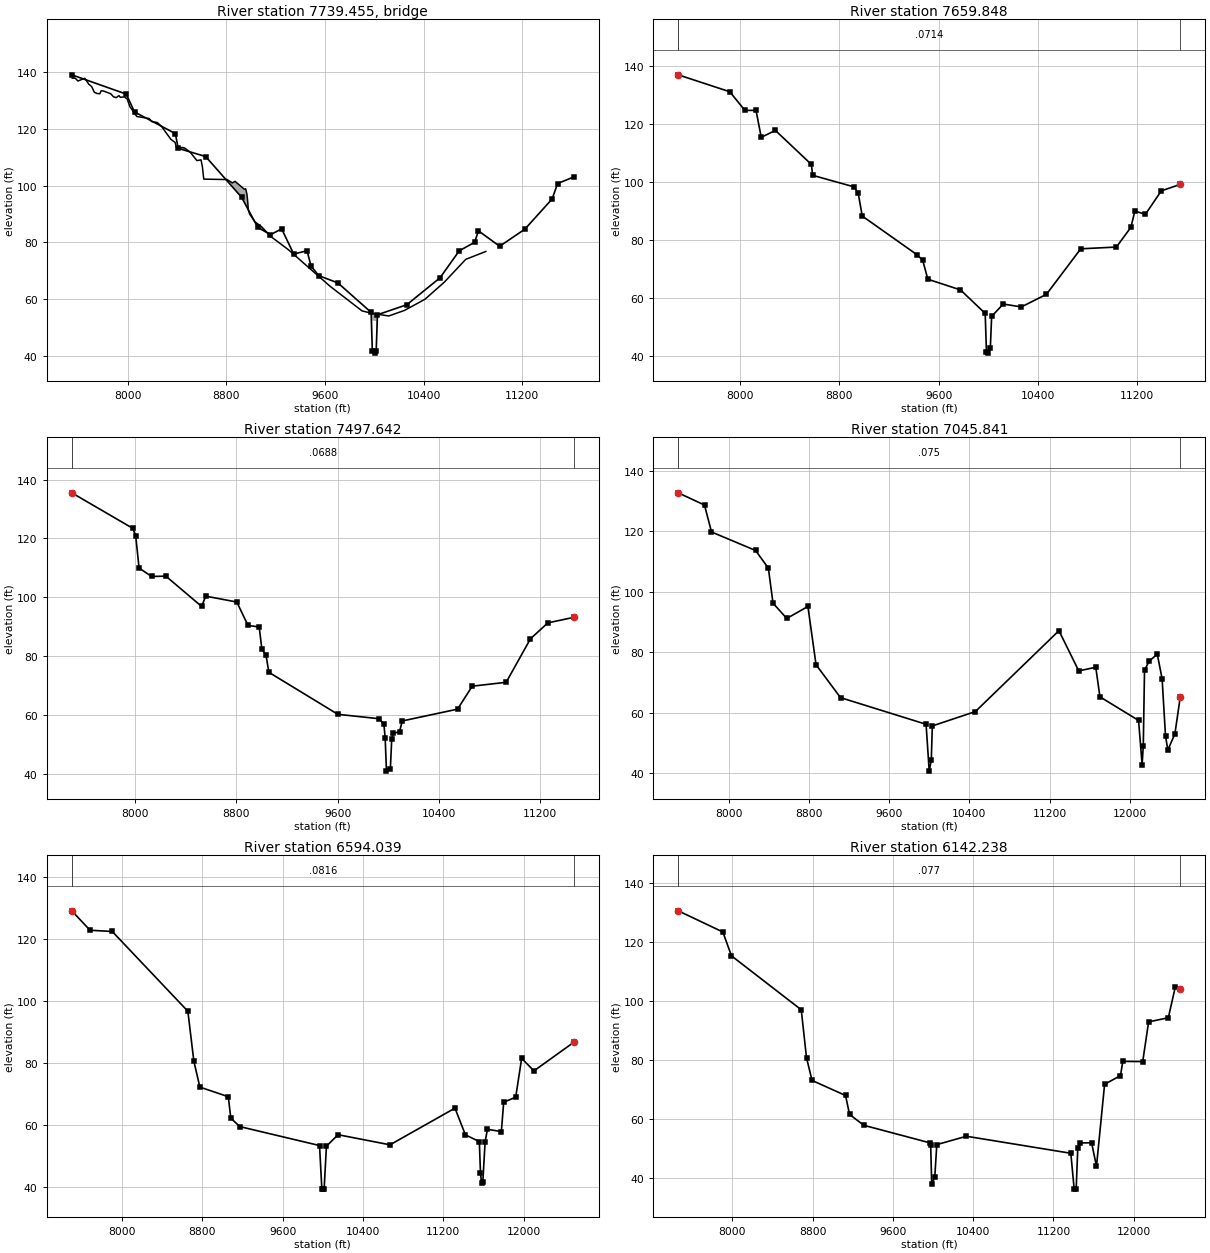
Type RM Length L Ch R = 3 ,7739.455,,,
BEGIN DESCRIPTION:
END DESCRIPTION:
Bridge Culvert--1,0,-1,-1, 0
Deck Dist Width WeirC Skew NumUp NumDn MinLoCord MaxHiCord MaxSubmerge Is_Ogee
48.135250,59.055000,2.6,0, 60, 60, , , 0.95, 0, 0,0,,
 7549.09 7573.16 7595.36 7650.85 7684.15 7706.73 7728.55 7750.75 7772.95 7784.05
 7798.92 7861.74 7883.94 7906.14 7928.34 7939.43 7972.73 7994.93 8017.13 8072.63
 8172.52 8194.72 8239.11 8272.41 8350.11 8383.41 8394.50 8405.60 8438.90 8461.10
 8505.50 8560.99 8594.29 8605.39 8616.49 8805.18 8848.36 8869.94 8945.49 8956.29
 8967.08 8973.61 8977.87 8988.67 9031.84 9085.80 9159.66 9301.66 9639.72 9900.70
 9983.60 9983.6010016.4010016.4010117.3710245.1910410.9910566.1010741.9010904.75
  137.74  137.76  136.75  137.71  135.59  134.82  132.80  132.37  132.27  133.32
  133.28  132.27  131.20  130.91  131.61  131.03  131.16  130.45  127.75  124.30
  123.58  122.49  122.17  120.86  116.22  115.19  113.50  112.76  113.42  113.19
  111.79  108.78  109.04  106.57  102.27  102.12  100.95  101.50   98.72   98.88
   96.91   94.07   91.45   89.99   87.24   85.52   82.13   77.52   64.67   55.96
   55.08   55.08   54.86   54.86   54.17   56.13   60.04   65.97   74.07   76.84
 -862.26 -862.24 -863.25 -862.29 -864.41 -865.18 -867.20 -867.63 -867.73 -866.68
 -866.72 -867.73 -868.80 -869.09 -868.39 -868.97 -868.84 -869.55 -872.25 -875.70
 -876.42 -877.51 -877.83 -879.14 -883.78 -884.81 -886.50 -887.24 -886.58 -886.81
 -888.21 -891.22 -890.96 -893.43 -897.73 -897.88 -899.05 -898.50 -901.28 -901.12
 -903.09 -905.93 -908.55 -910.01 -912.76 -914.48 -917.87 -922.48 -935.33 -944.04
 -944.92   52.58   52.36 -945.14 -945.83 -943.87 -939.96 -934.03 -925.93 -923.16
 7549.09 7573.16 7595.36 7650.85 7684.15 7706.73 7728.55 7750.75 7772.95 7784.05
 7798.92 7861.74 7883.94 7906.14 7928.34 7939.43 7972.73 7994.93 8017.13 8072.63
 8172.52 8194.72 8239.11 8272.41 8350.11 8383.41 8394.50 8405.60 8438.90 8461.10
 8505.50 8560.99 8594.29 8605.39 8616.49 8805.18 8848.36 8869.94 8945.49 8956.29
 8967.08 8973.61 8977.87 8988.67 9031.84 9085.80 9159.66 9301.66 9639.72 9900.70
 9983.60 9983.6010016.4010016.4010117.3710245.1910410.9910566.1010741.9010904.75
  137.74  137.76  136.75  137.71  135.59  134.82  132.80  132.37  132.27  133.32
  133.28  132.27  131.20  130.91  131.61  131.03  131.16  130.45  127.75  124.30
  123.58  122.49  122.17  120.86  116.22  115.19  113.50  112.76  113.42  113.19
  111.79  108.78  109.04  106.57  102.27  102.12  100.95  101.50   98.72   98.88
   96.91   94.07   91.45   89.99   87.24   85.52   82.13   77.52   64.67   55.96
   55.08   55.08   54.86   54.86   54.17   56.13   60.04   65.97   74.07   76.84
 -862.26 -862.24 -863.25 -862.29 -864.41 -865.18 -867.20 -867.63 -867.73 -866.68
 -866.72 -867.73 -868.80 -869.09 -868.39 -868.97 -868.84 -869.55 -872.25 -875.70
 -876.42 -877.51 -877.83 -879.14 -883.78 -884.81 -886.50 -887.24 -886.58 -886.81
 -888.21 -891.22 -890.96 -893.43 -897.73 -897.88 -899.05 -898.50 -901.28 -901.12
 -903.09 -905.93 -908.55 -910.01 -912.76 -914.48 -917.87 -922.48 -935.33 -944.04
 -944.92   52.58   52.36 -945.14 -945.83 -943.87 -939.96 -934.03 -925.93 -923.16
BR Coef=-1 , 0 , 0 ,, 0 ,,,0.8,0,1,0,
WSPro=,,,, 1 ,,,, 0 ,,,, 0 ,,,,-1 ,-1 ,-1 , 0 , 0 , 0 , 0 , 0
BC Design=,, 0 ,, 0 ,,,,,,

Type RM Length L Ch R = 1 ,7659.848,162.206100,162.206100,162.206100
XS GIS Cut Line= 6
747050.024238706856677.587794304747677.802016526855399.810016498
747888.913127631854884.532238737748018.600627571854488.525294289
748118.427016497854139.393349826748560.985150665852932.414477333
#Sta/Elev= 30
7501.539 137.1187916.666131.28288039.225124.83498128.359124.8672 8170.48115.5508
8284.343117.94048574.028106.22678585.169102.44078918.849 98.45058952.01596.26998
8984.435 88.39659427.51274.988199471.72973.123379513.12666.593629776.19162.90974
9975.22454.804299985.62541.434799994.78241.0964910016.8342.9316310027.2353.76724
10120.8358.0331210266.5557.0380410468.71 61.372410745.3577.0881411032.6277.69669
11149.6684.5163711181.5890.10922 11266.7 88.999911394.3897.0806511547.8299.31882
#Mann= 3 , 0 , 0
7501.539  0.0714       07501.539  0.0714       011547.82  0.0714       0
#XS Ineff= 2 , 0
       0                10464.48       0
Bank Sta=7501.539,11547.82
Exp/Cntr=0.3,0.1

Type RM Length L Ch R = 1 ,7497.642,451.801300,451.801300,451.801300
XS GIS Cut Line= 6
747185.767052501  856706.3504695747607.267461896855936.889352679
747938.567469597855245.433858559 748095.37868908854816.912904009
748403.202770561853762.396763682748716.947310239853061.570640713
#Sta/Elev= 30
7499.035135.51527981.815123.42188004.599120.71638031.028109.94958129.514107.0611
8242.721107.17558524.698 96.89198558.205100.36488803.43798.374998891.83490.40682
8980.06789.892229001.90182.290259034.65380.242219056.487 74.47429601.82660.17954
    992458.696949965.44356.944669975.804  52.2379986.16540.8526410017.2541.73647
10027.6251.6669210037.9853.67795 10089.854.2765210110.5357.9145510547.9261.93363
10664.1469.7488710932.2271.06808 11124.485.8757911261.41 91.278911467.1293.15964
#Mann= 3 , 0 , 0
7499.035  0.0688       07499.035  0.0688       011467.12  0.0688       0
#XS Ineff= 2 , 0
       0                10463.41       0
Bank Sta=7499.035,11467.12
Exp/Cntr=0.3,0.1

Type RM Length L Ch R = 1 ,7045.841,451.801400,451.801400,451.801400
XS GIS Cut Line= 6
747479.765615211856750.429876498748438.843714271855092.410227678
748562.608544135854806.473279781748957.126116975853650.373087382
749268.972985558 853027.47492893749699.080046323852289.009979079
#Sta/Elev= 30
7499.044132.7746 7760.75128.71997830.376119.81398269.869113.6749 8397.09107.8146
8443.35396.217698580.47491.168278790.86195.138248871.996  75.833 9115.8864.93868
9968.25956.118829999.35940.6019210020.0644.2119910030.4155.5692110459.1260.32497
11291.8787.11605 11489.273.7904911658.7775.0104511700.1965.2084912085.1557.38946
12120.4742.7546712132.0949.0223612144.3273.9960212190.1977.03376 12271.779.33365
12319.6671.1703912353.5952.1522712376.9847.6001612447.1752.9636612500.9765.28806
#Mann= 3 , 0 , 0
7499.044   0.075       07499.044   0.075       012500.97   0.075       0
#XS Ineff= 2 , 0
       0                10613.08       0
Bank Sta=7499.044,12500.97
Exp/Cntr=0.3,0.1

Type RM Length L Ch R = 1 ,6594.039,451.801300,451.801300,451.801300
XS GIS Cut Line= 6
747665.255810166856751.399715717748320.343121371855686.504607041
748523.410826358855403.166623855748902.738870538854937.030324141
749010.023556029854787.289637334750343.782430176852535.200590502
#Sta/Elev= 30
7499.054129.1893  7681.2122.92487902.477122.52748655.50496.818298715.35980.71619
8775.09972.363599058.50169.262069083.37862.366299172.19959.635849967.38653.51741
9990.31639.61014    999939.4677710013.2639.5891410036.1753.3019110151.6857.01244
10669.4653.75543 11316.765.5796511420.6956.9637711559.3654.8078811570.9144.55593
11582.57 41.384511594.0241.7223311617.1354.8093511640.2458.7595611778.9158.01914
11802.0267.4934511921.8569.1026411980.9581.6284212103.6777.5995512500.9886.82091
#Mann= 3 , 0 , 0
7499.054  0.0816       07499.054  0.0816       012500.98  0.0816       0
#XS Ineff= 2 , 0
       0                10493.45       0
Bank Sta=7499.054,12500.98
Exp/Cntr=0.3,0.1

Type RM Length L Ch R = 1 ,6142.238,360.291800,360.291800,360.291800
XS GIS Cut Line= 6
747674.290168687856847.339075929748679.153260618855356.417507441
749001.962077429855127.795749189749552.977317821854973.698965766
749792.922576687854777.616897808750788.244864486853143.016229694
#Sta/Elev= 30
7461.755130.62727906.347123.43267992.107115.3299  8687.397.005658739.644  80.683
8794.786 73.00069128.65667.882939168.45261.443869310.49357.76354 9966.5851.81768
9976.72150.938879986.86337.7144110017.2940.05389 10037.651.1949510332.79 54.0355
11372.7548.2536111406.2236.0715211426.4236.28101 11441.849.8833911464.8251.76267
11579.9151.8248711628.4443.8218311709.2571.6857411867.6374.6509811890.6479.48086
12088.8979.4003512147.8692.9004812343.9994.2936112414.31104.860812463.53103.9614
#Mann= 3 , 0 , 0
7461.755   0.077       07461.755   0.077       012463.53   0.077       0
#XS Ineff= 2 , 0
       0                10664.09       0
Bank Sta=7461.755,12463.53
Exp/Cntr=0.3,0.1

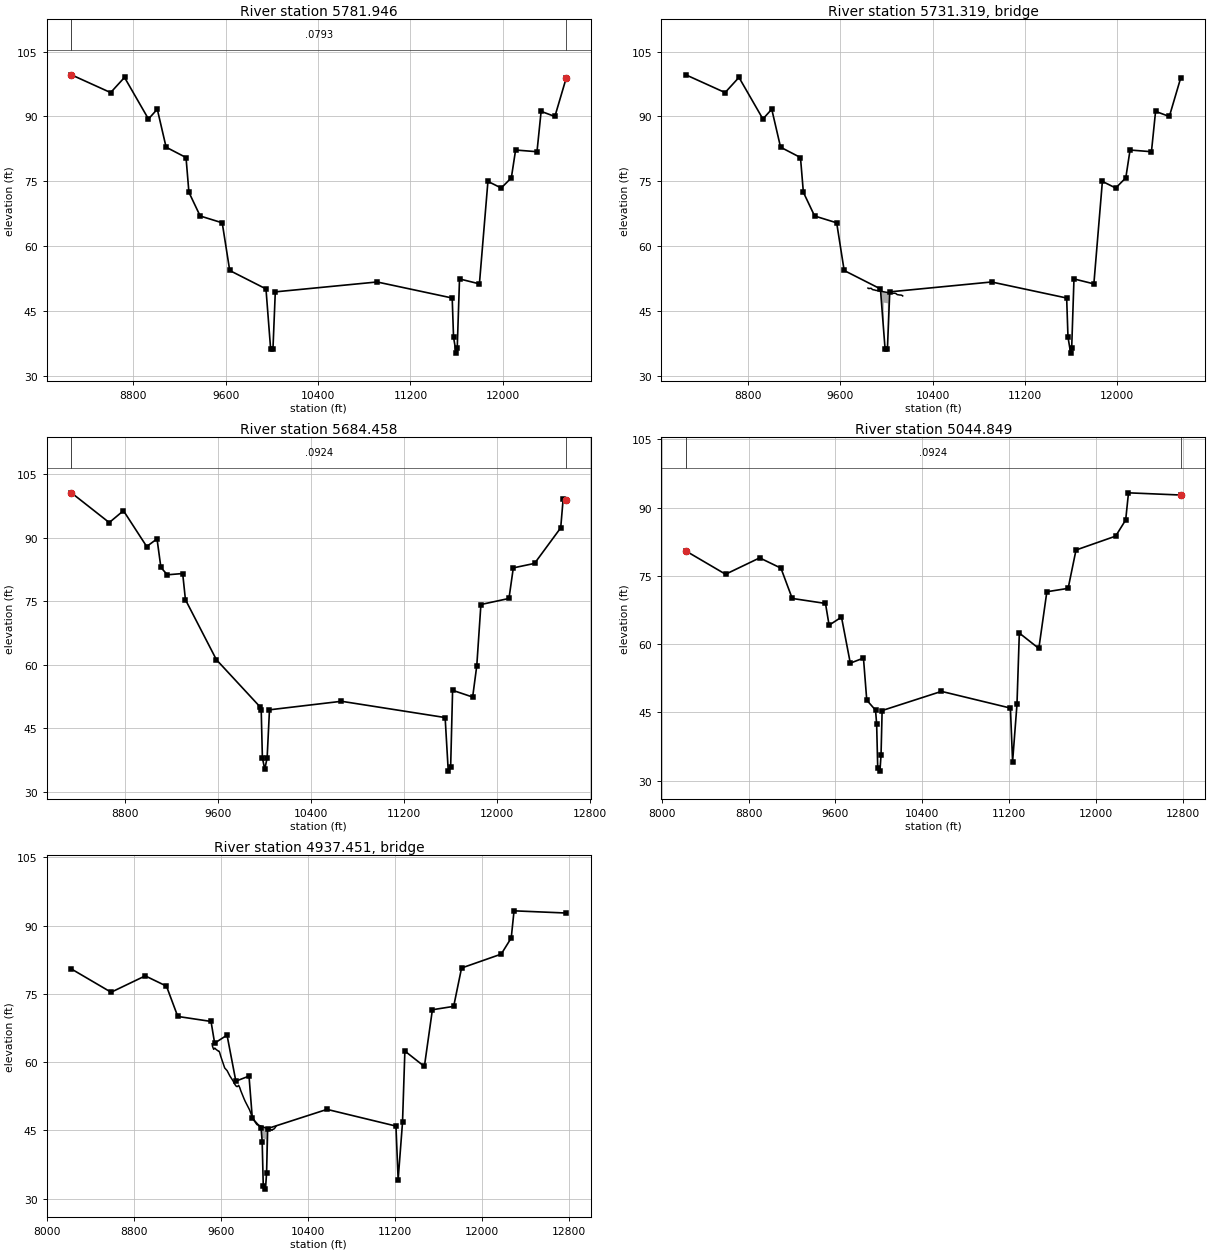
Type RM Length L Ch R = 1 ,5781.946,97.487700,97.487700,97.487700
XS GIS Cut Line= 6
748507.894609094856816.129460946749012.061275721855661.962794289
749270.394609153855411.962794259749527.339053541855380.018349826
749705.909990132855252.043049589750852.802016497853392.518349826
#Sta/Elev= 30
8265.17499.607848604.69395.49983 8724.7399.013138932.06689.390669008.45391.66404
 9084.84 82.87359257.19980.48306 9282.1872.449749379.47666.96272 9570.4965.38379
9635.32354.357819949.24950.100589989.55736.1919510009.7136.2171110029.8749.41447
10911.2251.7020811561.0847.9920511572.6638.9360611595.8235.24756 11604.636.42441
11624.4452.4077711796.5751.2638211870.2774.96452 11985.473.4320912072.9475.78723
12109.7982.2180212294.9681.8264612330.6891.1581112449.7489.9727112547.9598.86609
#Mann= 3 , 0 , 0
8265.174  0.0793       08265.174  0.0793       012547.95  0.0793       0
#XS Ineff= 2 , 0
       0                10901.01       0
Bank Sta=8265.174,12547.95
Exp/Cntr=0.3,0.1

Type RM Length L Ch R = 3 ,5731.319,,,
BEGIN DESCRIPTION:
END DESCRIPTION:
Bridge Culvert--1,0,-1,-1, 0
Deck Dist Width WeirC Skew NumUp NumDn MinLoCord MaxHiCord MaxSubmerge Is_Ogee
16.243850,65.000000,2.6,0, 31, 31, , , 0.95, 0, 0,0,,
 9841.24 9846.24 9849.31 9859.51 9869.71 9879.91 9890.11 9896.88 9900.31 9910.51
 9920.72 9930.92 9935.15 9978.21 9978.2110013.2110013.2110041.2910043.1310048.82
10053.3310063.5310073.7310083.9310094.1310099.4710104.3310114.5310124.7310134.93
10141.95
   50.29   50.21   50.17   50.23   50.23   49.95   49.88   49.86   49.84   49.74
   49.74   49.71   49.65   49.43   49.43   49.26   49.26   49.12   49.12   49.13
   49.11   49.07   49.11   49.01   48.79   48.75   48.74   48.69   48.68   48.62
   48.47
 -949.71 -949.79 -949.83 -949.77 -949.77 -950.05 -950.12 -950.14 -950.16 -950.26
 -950.26 -950.29 -950.35 -950.57   46.93   46.76 -950.74 -950.88 -950.88 -950.87
 -950.89 -950.93 -950.89 -950.99 -951.21 -951.25 -951.26 -951.31 -951.32 -951.38
 -951.53
 9841.24 9846.24 9849.31 9859.51 9869.71 9879.91 9890.11 9896.88 9900.31 9910.51
 9920.72 9930.92 9935.15 9969.96 9969.9610004.9610004.9610041.2910043.1310048.82
10053.3310063.5310073.7310083.9310094.1310099.4710104.3310114.5310124.7310134.93
10141.95
   50.29   50.21   50.17   50.23   50.23   49.95   49.88   49.86   49.84   49.74
   49.74   49.71   49.65   49.47   49.47   49.30   49.30   49.12   49.12   49.13
   49.11   49.07   49.11   49.01   48.79   48.75   48.74   48.69   48.68   48.62
   48.47
 -949.71 -949.79 -949.83 -949.77 -949.77 -950.05 -950.12 -950.14 -950.16 -950.26
 -950.26 -950.29 -950.35 -950.53   46.97   46.80 -950.70 -950.88 -950.88 -950.87
 -950.89 -950.93 -950.89 -950.99 -951.21 -951.25 -951.26 -951.31 -951.32 -951.38
 -951.53
BR Coef=-1 , 0 , 0 ,, 0 ,,,0.8,0,1,0,
WSPro=,,,, 1 ,,,, 0 ,,,, 0 ,,,,-1 ,-1 ,-1 , 0 , 0 , 0 , 0 , 0
BC Design=,, 0 ,, 0 ,,,,,,

Type RM Length L Ch R = 1 ,5684.458,639.610000,639.610000,639.610000
XS GIS Cut Line= 6
748556.852942377856848.073905393 749102.68627575855723.073905393
749319.352942377855506.407238707 749540.18627575855464.740572035
749779.769609094855300.157238707750919.005720198853434.879460916
#Sta/Elev= 30
8337.563100.62398663.31193.597168785.57596.405638985.64287.942729074.56189.74998
9107.90682.99234 9163.4881.268169295.47681.563479319.08975.389819585.84661.20821
9961.20550.086589971.38149.288329981.55838.0232210001.9135.3530210022.2638.01788
10042.6249.3831610662.4351.3962811554.5947.5547211581.4734.9028711601.9635.78082
 11618.853.9924911791.4552.3965811826.9859.7703311862.5174.2460612104.1275.68134
12141.4582.8998812324.3883.9569712549.3992.3507212570.7799.2471412596.9199.03069
#Mann= 3 , 0 , 0
8337.563  0.0924       08337.563  0.0924       012596.91  0.0924       0
#XS Ineff= 2 , 0
       0                10942.39       0
Bank Sta=8337.563,12596.91
Exp/Cntr=0.3,0.1

Type RM Length L Ch R = 1 ,5044.849,174.166300,174.166300,174.166300
XS GIS Cut Line= 6
749065.880720198856974.462794274749754.769609094856418.907238707
750010.325164646856096.685016483749965.880720168 855388.35168317
750045.741831303855162.657238722751267.964053512853218.212794289
#Sta/Elev= 30
8222.22980.48671 8587.7675.37377 8901.9778.970999097.51576.717779201.55170.05498
9507.86968.956689541.001 64.17759655.23265.953849736.28455.835659857.56256.94945
9887.88247.696529968.734  45.512 9978.8442.476689988.94732.7006210009.16  32.106
10019.2735.5863810029.3745.4188910575.7549.6318311210.5345.9628111230.6734.19287
11270.9446.7723611292.6662.44888 11472.359.0642911546.1371.5286211741.99 72.2692
11814.6180.69857 12179.883.7532212271.9787.3053612297.8693.2668712778.3192.78247
#Mann= 3 , 0 , 0
8222.229  0.0924       08222.229  0.0924       012778.31  0.0924       0
#XS Ineff= 2 , 0
       0                 10719.4       0
Bank Sta=8222.229,12778.31
Exp/Cntr=0.3,0.1

Type RM Length L Ch R = 3 ,4937.451,,,
BEGIN DESCRIPTION:
END DESCRIPTION:
Bridge Culvert--1,0,-1,-1, 0
Deck Dist Width WeirC Skew NumUp NumDn MinLoCord MaxHiCord MaxSubmerge Is_Ogee
65.757750,42.650800,2.6,0, 35, 35, , , 0.95, 0, 0,0,,
 9517.50 9521.37 9532.13 9542.88 9553.63 9575.14 9579.41 9585.89 9596.64 9633.84
 9656.08 9681.03 9711.30 9721.40 9731.49 9741.58 9751.67 9761.77 9771.86 9781.95
 9812.23 9822.32 9862.69 9882.88 9903.06 9930.33 9983.60 9983.6010016.4010016.40
10069.9810074.6410086.6210094.8210105.93
   64.05   63.49   62.83   63.10   62.82   62.44   62.46   62.23   61.34   58.73
   58.14   56.98   55.87   55.37   54.98   54.68   54.65   54.92   54.44   53.72
   51.94   51.40   49.52   48.23   47.24   46.29   45.81   45.81   45.51   45.51
   45.03   45.21   45.31   45.51   45.91
 -935.95 -936.51 -937.17 -936.90 -937.18 -937.56 -937.54 -937.77 -938.66 -941.27
 -941.86 -943.02 -944.13 -944.63 -945.02 -945.32 -945.35 -945.08 -945.56 -946.28
 -948.06 -948.60 -950.48 -951.77 -952.76 -953.71 -954.19   43.31   43.01 -954.49
 -954.97 -954.79 -954.69 -954.49 -954.09
 9517.50 9521.37 9532.13 9542.88 9553.63 9575.14 9579.41 9585.89 9596.64 9633.84
 9656.08 9681.03 9711.30 9721.40 9731.49 9741.58 9751.67 9761.77 9771.86 9781.95
 9812.23 9822.32 9862.69 9882.88 9903.06 9930.33 9983.60 9983.6010016.4010016.40
10069.9810074.6410086.6210094.8210105.93
   64.05   63.49   62.83   63.10   62.82   62.44   62.46   62.23   61.34   58.73
   58.14   56.98   55.87   55.37   54.98   54.68   54.65   54.92   54.44   53.72
   51.94   51.40   49.52   48.23   47.24   46.29   45.81   45.81   45.51   45.51
   45.03   45.21   45.31   45.51   45.91
 -935.95 -936.51 -937.17 -936.90 -937.18 -937.56 -937.54 -937.77 -938.66 -941.27
 -941.86 -943.02 -944.13 -944.63 -945.02 -945.32 -945.35 -945.08 -945.56 -946.28
 -948.06 -948.60 -950.48 -951.77 -952.76 -953.71 -954.19   43.31   43.01 -954.49
 -954.97 -954.79 -954.69 -954.49 -954.09
BR Coef=-1 , 0 , 0 ,, 0 ,,,0.8,0,1,0,
WSPro=,,,, 1 ,,,, 0 ,,,, 0 ,,,,-1 ,-1 ,-1 , 0 , 0 , 0 , 0 , 0
BC Design=,, 0 ,, 0 ,,,,,,