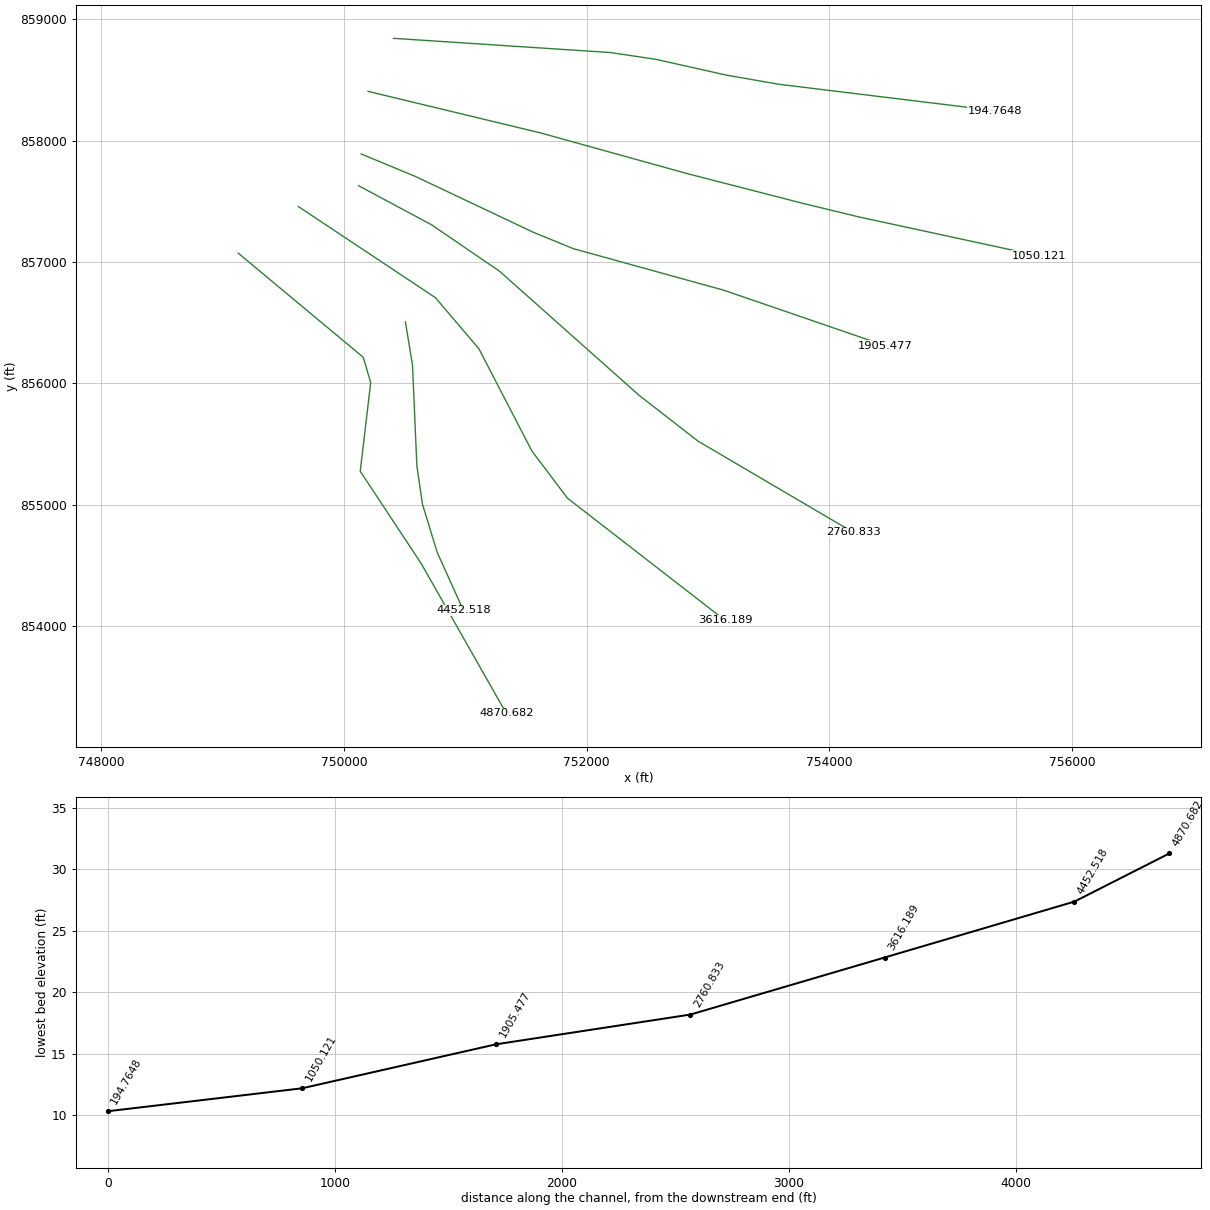
HEC-RAS study 15203_ras.prj: 15203

--- 15203_ras.g01 (geometry) --- (continued)

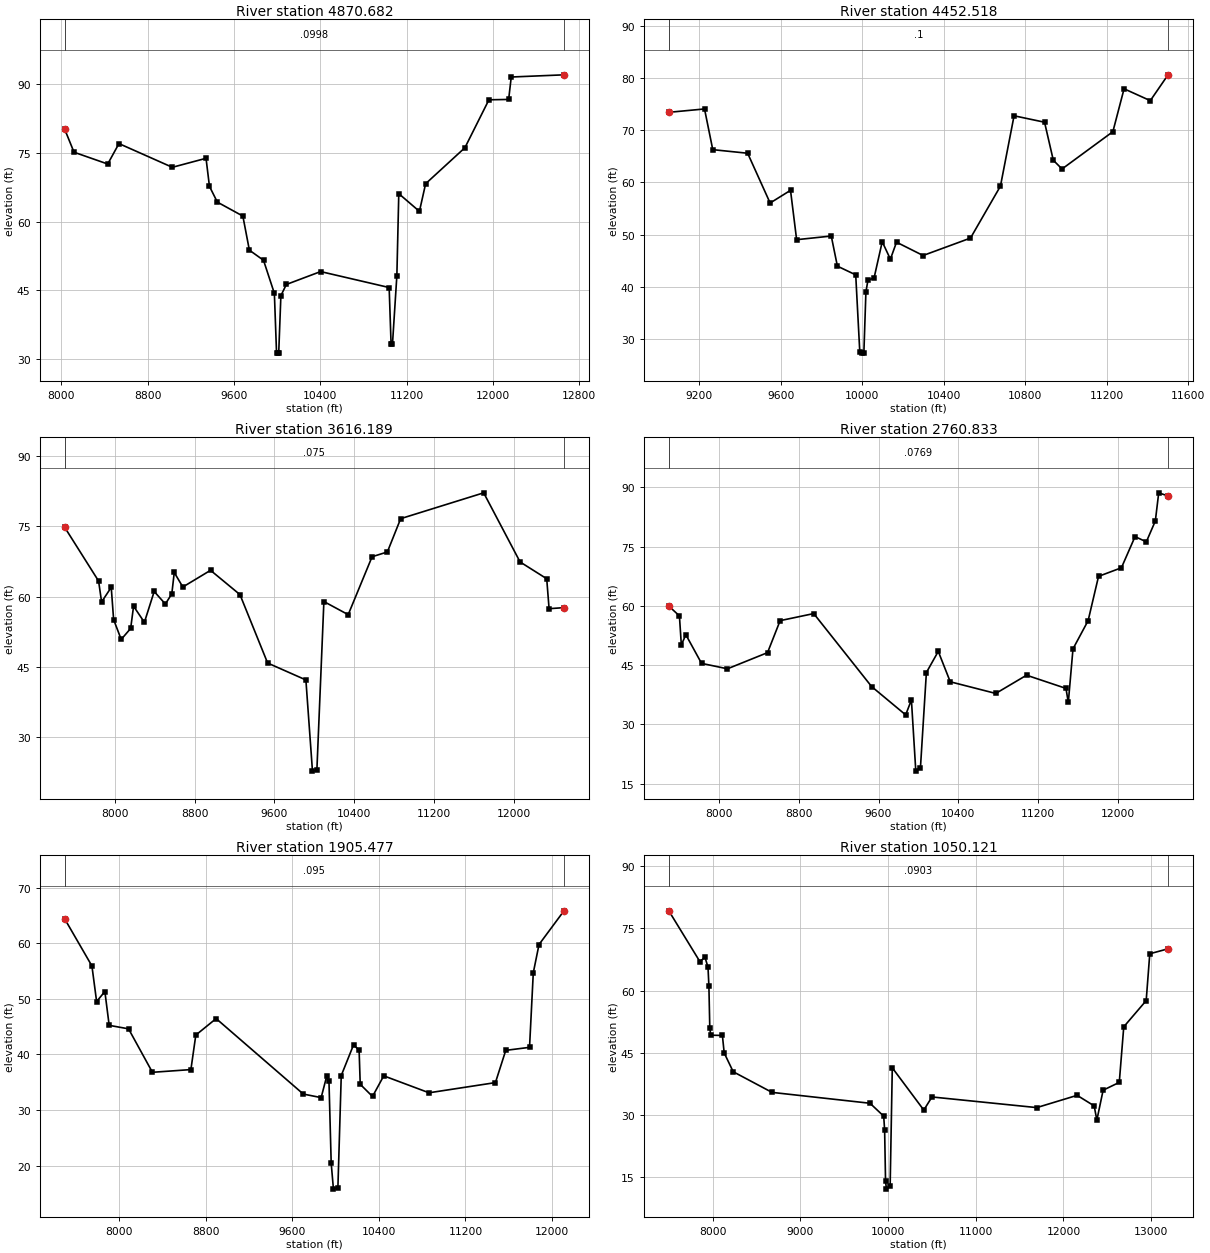
Type RM Length L Ch R = 1 ,4870.682,418.164300,418.164300,418.164300
XS GIS Cut Line= 6
749129.075164616857073.073905393750159.630720168 856214.74057205
750220.741831303856006.407238722750134.630720168 855275.85168317
750638.102942467854513.351683155751338.102942437853280.018349826
#Sta/Elev= 30
 8031.3480.151198117.13675.166828429.47772.589688533.59177.052149028.36171.87101
9340.47273.838339372.12167.715119445.20664.268089681.67861.217539742.09353.76813
9872.99351.564549973.686 44.32679993.82431.3402210003.89 31.275110013.9631.35014
 10034.143.8274210084.4546.2719510402.07 49.091211037.3345.6061411055.1833.21913
11068.0933.25696 11108.748.1928311126.5466.1147811317.7362.2450511375.2268.28298
11739.3276.1516511961.64 86.618212144.5186.6968912168.6191.5975512657.2792.07433
#Mann= 3 , 0 , 0
 8031.34  0.0998       0 8031.34  0.0998       012657.27  0.0998       0
#XS Ineff= 2 , 0
       0                10597.17       0
Bank Sta=8031.34,12657.27
Exp/Cntr=0.3,0.1

Type RM Length L Ch R = 1 ,4452.518,836.328700,836.328700,836.328700
XS GIS Cut Line= 6
750507.084590248856506.983075887750565.603990559856147.731669523
 750601.29229528855319.555561569750647.666301759855003.001998951
750769.299828498854606.545585201750983.814700547854130.904295135
#Sta/Elev= 30
 9050.3773.419019225.68174.06294 9266.1566.277549437.389 65.59229547.70856.07424
9647.80158.497449677.82149.057799847.85649.75676 9877.8643.998219967.87942.33117
9987.89527.535179997.90427.3608810007.9127.4758910017.9339.0906510027.9441.30004
10057.97  41.74510098.0248.6690510138.0745.3264510168.1348.5799510298.5346.03227
10531.2949.3652910678.3259.3048310745.1472.7568210894.7871.5255410937.8164.24979
10980.6362.5826511230.2269.7186211285.1377.9210611413.8875.6492211500.9680.59045
#Mann= 3 , 0 , 0
 9050.37     0.1       0 9050.37     0.1       011500.96     0.1       0
#XS Ineff= 2 , 0
       0                10238.44       0
Bank Sta=9050.37,11500.96
Exp/Cntr=0.3,0.1

Type RM Length L Ch R = 1 ,3616.189,855.356100,855.356100,855.356100
XS GIS Cut Line= 6
  749624.8182604 857457.36433586750754.036918372856706.616352017
751112.797851081856285.346055176 751549.00776132855443.307903657
751842.564698046855053.915854706753141.577642108854046.721559121
#Sta/Elev= 30
7499.03974.76515  7838.163.334117868.08858.875517964.77261.996867988.62755.12454
8064.49250.889348159.324 53.23078188.57257.967958297.04754.53762  8395.161.11297
8507.06658.435498571.754 60.61748596.16965.160428682.109 62.06498959.714  65.623
9254.57160.442549531.60445.861869915.05142.254049981.01522.8174110025.0923.01832
10095.3958.9663410338.9256.1701310578.18 68.513210731.4569.5366410864.6176.63146
11696.3782.13904 12061.167.4031612327.9363.8269212351.6657.4408612500.94 57.6674
#Mann= 3 , 0 , 0
7499.039   0.075       07499.039   0.075       012500.94   0.075       0
#XS Ineff= 2 , 0
       09767.702                       0
Bank Sta=7499.039,12500.94
Exp/Cntr=0.3,0.1

Type RM Length L Ch R = 1 ,2760.833,855.356100,855.356100,855.356100
XS GIS Cut Line= 6
750121.726561636857628.794765504 750722.73053944857307.017758133
751283.187368822856924.094354858752433.120437212855901.538064707
752920.790445101855522.657831187754198.510296075854771.816781662
#Sta/Elev= 30
7499.04559.950647605.32157.462547624.63450.104067669.565 52.71277827.01745.45201
8086.44444.075688488.29148.166618614.32356.260558951.10558.051639530.985  39.584
9872.26132.411989929.78536.196489973.70418.1826810020.3419.0675810079.7143.12593
10198.8748.4817810318.8340.7894910774.7237.84043 11083.3 42.457111478.2439.11911
11501.7635.55303 11548.649.1198511700.2356.2586711804.5867.4695512033.8869.64158
12170.5177.5288712283.44 76.201112373.7381.48402 12407.588.6059712500.9787.81808
#Mann= 3 , 0 , 0
7499.045  0.0769       07499.045  0.0769       012500.97  0.0769       0
#XS Ineff= 2 , 0
       09673.558        10145.79       0
Bank Sta=7499.045,12500.97
Exp/Cntr=0.3,0.1

Type RM Length L Ch R = 1 ,1905.477,855.356100,855.356100,855.356100
XS GIS Cut Line= 6
750142.069092984857890.997080577750587.685776641857706.422414642
751560.448543953857245.752440171751890.545179864857110.551218415
753132.781472634856767.428096638754462.850513565856310.494753839
#Sta/Elev= 30
7499.03964.386767750.01455.933117793.32349.53256 7869.5751.334567909.32945.24544
8088.25444.617598308.73736.795048664.20337.282778709.53343.491678897.30346.46238
9702.33732.879139867.338 32.23789918.90136.110919939.52635.168759960.15120.40039
9980.77615.7691710022.0216.0509510052.9536.2128610166.3641.7299210217.9140.76751
10228.2234.6380910341.6332.4420610445.4536.1593510863.7833.1078411477.0934.94069
11572.4340.7432211792.0441.2859411826.6754.7041111879.6459.7915112110.23  65.855
#Mann= 3 , 0 , 0
7499.039   0.095       07499.039   0.095       012110.23   0.095       0
#XS Ineff= 2 , 0
       09243.404        10156.55       0
Bank Sta=7499.039,12110.23
Exp/Cntr=0.3,0.1

Type RM Length L Ch R = 1 ,1050.121,855.356100,855.356100,855.356100
XS GIS Cut Line= 6
750199.362684786858406.779832065751623.210153222858063.834674284
752838.330506682857726.722308815753774.069355905857486.039108351
754236.485001653857373.805425361755728.643025815857051.004158884
#Sta/Elev= 30
7499.01479.206847853.46366.985737911.50768.026437945.90265.648627956.17361.20806
7966.444 51.06527976.71549.259998110.23949.196288130.78144.982898233.66240.45619
8676.542 35.48699794.08732.868739950.24229.763379960.72526.420249971.20814.10095
 9981.6912.1916110023.6112.8480910048.2241.4007710407.6431.2265810500.7934.38605
11696.0331.8226212156.4434.7771112350.83 32.237812381.5228.8086112453.1436.01605
12637.31 37.894512688.4651.2787712944.2557.5867412985.1768.8667413193.5370.06021
#Mann= 3 , 0 , 0
7499.014  0.0903       07499.014  0.0903       013193.53  0.0903       0
#XS Ineff= 2 , 0
       0 8916.96        10123.94       0
Bank Sta=7499.014,13193.53
Exp/Cntr=0.3,0.1

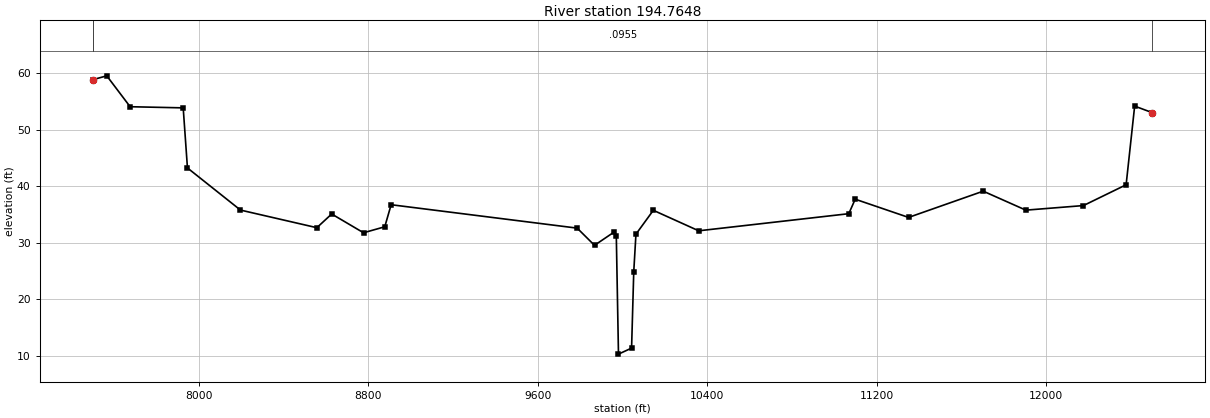
Type RM Length L Ch R = 1 ,194.7648,0.000000,0.000000,0.000000
XS GIS Cut Line= 6
750409.089200805858844.010426395752197.853195391858726.905010796
752570.886102322858671.031025476753149.174296757858541.461797715
753580.727281585858466.047930276755368.378574579858247.651976126
#Sta/Elev= 30
7499.05358.803727565.12459.485987675.39254.028757925.899 53.82667945.93443.21505
8196.27735.77302 8556.7532.661458626.84535.081928777.11931.766388877.31932.82194
8907.40736.718689785.61732.583699867.35229.546999959.96731.891469970.25831.25089
9980.54910.3295510042.3711.3937710052.6724.9108710062.98 31.513110145.0135.73334
10359.3232.1124511067.6835.1342811097.9237.6943711349.8434.4764111702.2239.11289
11903.57 35.7609 12175.436.5700312376.7640.2435212417.0354.1376612500.9752.97032
#Mann= 3 , 0 , 0
7499.053  0.0955       07499.053  0.0955       012500.97  0.0955       0
#XS Ineff= 2 , 0
       08469.899        10145.98       0
Bank Sta=7499.053,12500.97
Exp/Cntr=0.3,0.1